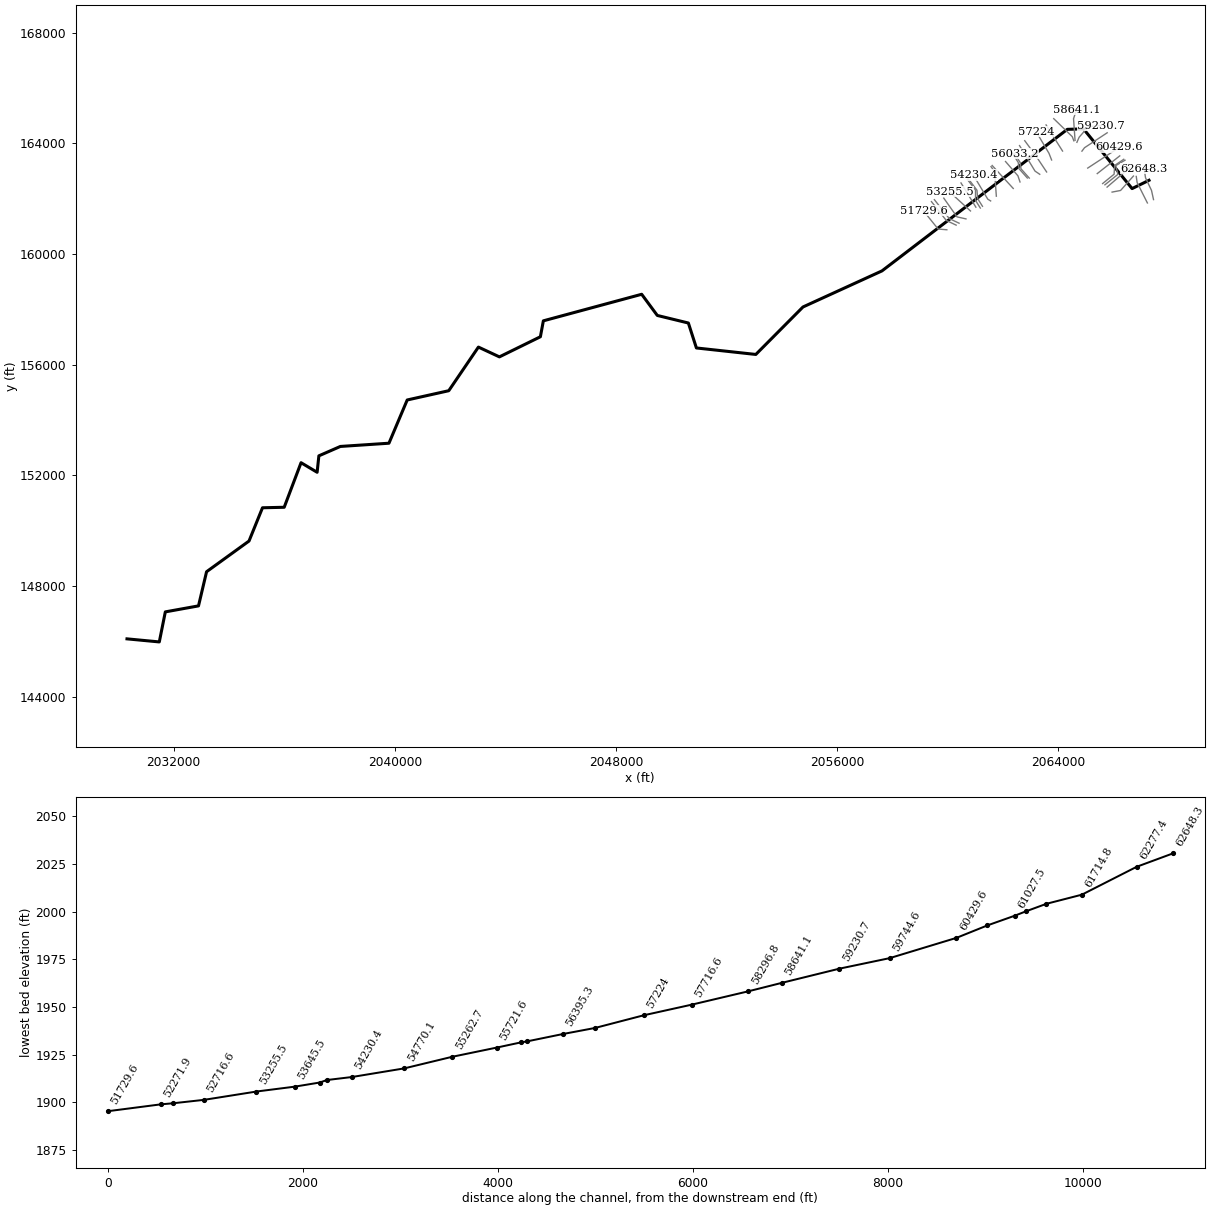
--- RICHCK.prj (project) ---

Proj Title=RICHCK
Current Plan=p01
Default Exp/Contr=0,0
English Units
Geom File=g01
Flow File=f01
Plan File=p01
BEGIN DESCRIPTION:
END DESCRIPTION:
DSS Export Rating Curves= 0
DSS Export Rating Curve Sorted= 0
DSS Export Volume Flow Curves= 0
DXF Filename=.\backup\RICHCK.
DXF OffsetX= 0
DXF OffsetY= 0
DXF ScaleX= 0
DXF ScaleY= 0

--- RICHCK.p01 (plan) ---

Plan Title=Floodplain
Program Version=4.00
Geom File=g01
Flow File=f01
K Sum by GR=0
Std Step Tol=0.01
Critical Tol=0.01
Num of Std Step Trials=20
Max Error Tol=0.3
Flow Tol Ratio=0.001
Split Flow NTrial=30
Split Flow Tol=0.02
Split Flow Ratio=0.02
Log Output Level=0
Friction Slope Method=1
Unsteady Friction Slope Method=2
Unsteady Bridges Friction Slope Method=1
Global Log Level=0
CheckData=False
Run HTab=0
Run UNet=0
Run PostProcess=0
UNET Theta=0
UNET Theta Warmup=0
UNET ZTol=0
UNET ZSATol=0
UNET MxIter=0
UNET MaxInSteps=0
UNET DtIC=0
UNET DtMin=0
UNET MaxCRTS=0
UNET WFStab=0
UNET SFStab=0
UNET WFX=0
UNET SFX=0
UNET DSS MLevel=0
UNET DZMax Abort=0
UNET Convert EG Bridges=0
UNET Use Existing IB Tables=0
UNET Froude Limit=0
UNET Froude Power=0
Write IC File=0
Echo Input=False
Echo Output=False
Write Detailed=0

--- RICHCK.f01 (steady flow) ---

Flow Title=NFF Regression Equation
Program Version=4.10
Number of Profiles= 1
Profile Names=P100yr
River Rch & RM=RICHCK,Main            ,62648.3
403.6507
River Rch & RM=RICHCK,Main            ,62277.4
545.8694
River Rch & RM=RICHCK,Main            ,61714.8
902.6369
River Rch & RM=RICHCK,Main            ,61714.8
547.1134
River Rch & RM=RICHCK,Main            ,61352.7
904.7664
River Rch & RM=RICHCK,Main            ,57716.6
1004.202
River Rch & RM=RICHCK,Main            ,55262.7
1072.021
River Rch & RM=RICHCK,Main            ,50349.7
1190.325
River Rch & RM=RICHCK,Main            ,44384.2
1305.225
River Rch & RM=RICHCK,Main            ,43716.2
1872.577
River Rch & RM=RICHCK,Main            ,41897.3
2130.221
River Rch & RM=RICHCK,Main            ,41897.3
1881.984
River Rch & RM=RICHCK,Main            ,35296
2548.707
River Rch & RM=RICHCK,Main            ,35296
2215.314
River Rch & RM=RICHCK,Main            ,23121.1
2821.319
River Rch & RM=RICHCK,Main            ,21861.5
3615.009
River Rch & RM=RICHCK,Main            ,19384
3725.243
River Rch & RM=RICHCK,Main            ,91.8
4117.296
Boundary for River Rch & Prof#=RICHCK,Main            , 1
Up Type= 0
Dn Type= 1
Dn Known WS=1699.32
DSS Import GetInterval= 0
DSS Import GetPeak= 0
DSS Import FillOption= 0

--- RICHCK.g01 (geometry) ---

Geom Title=USGS 10m DEM
Program Version=4.10

River Reach=RICHCK          ,Main
Reach XY= 30
     2067281.909      162662.622      2066669.93      162362.275
     2064911.683      164520.261     2064327.481      164504.202
     2057623.098      159387.506     2054765.893      158083.339
     2053059.817      156367.411     2050910.591      156601.809
     2050620.139      157503.545     2049496.528      157777.156
      2048931.65      158542.407     2045375.254      157582.455
     2045267.607      157006.777     2043785.316      156279.694
     2043025.941      156633.513      2041953.43      155056.663
     2040450.652      154721.572     2039790.235      153158.812
     2038032.683      153041.942     2037255.226      152702.556
     2037192.406      152107.915     2036611.155      152454.442
     2036001.317      150843.302     2035216.422      150825.594
     2034728.586      149622.955     2033193.619      148514.018
     2032901.676      147278.945     2031701.676      147062.278
     2031483.569      145976.265     2030315.209      146086.971

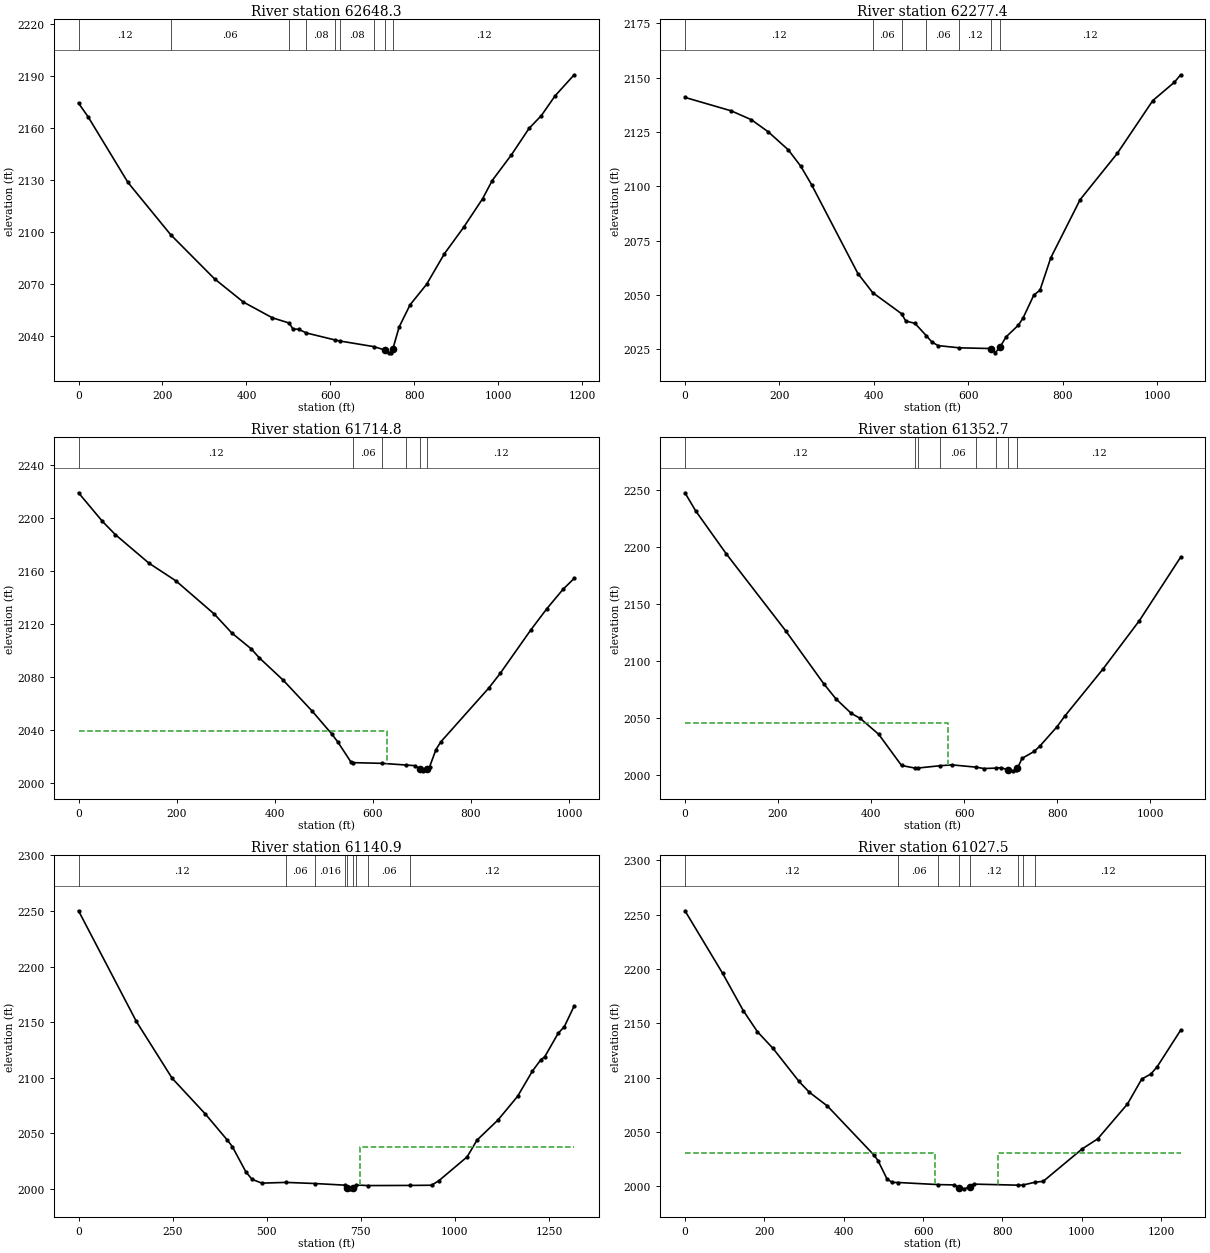
Type RM Length L Ch R = 1 ,62648.3 ,370.2,370.9,370.9
XS GIS Cut Line= 4
     2067444.812      161964.894     2067371.541       162297.17
     2067156.183      162750.485       2067104.1      163084.686
#Sta/Elev= 30
       0 2174.46    22.9 2166.54   117.8 2128.69  219.422098.603   323.9 2073.14
   392.7 2059.73   461.6 2050.67  501.632047.656   510.8 2044.17     524 2044.07
   542.62041.927  610.75 2037.89  623.222037.257  703.332034.045   730.6 2032.01
   740.4 2030.46   743.7 2030.56  748.92 2032.96   763.4 2045.27   789.6 2058.14
     829    2070   871.4 2087.62   916.9 2102.75   962.5 2119.39   985.2 2129.82
  1030.8 2144.58    1073  2159.9  1102.3 2167.28  1134.8 2178.61  1180.4  2190.8
#Mann= 9 ,-1 , 0
       0     .12       0  219.42     .06       0  501.63    .016       0
   542.6     .08       0  610.75     .12       0  623.22     .08       0
  703.33     .12       0   730.6    .045       0  748.92     .12       0
Bank Sta=730.6,748.92
XS Rating Curve= 0 ,0
Exp/Cntr=0.3,0.1

Type RM Length L Ch R = 1 ,62277.4 ,587.4,562.6,538.1
XS GIS Cut Line= 3
     2067222.972      161843.511     2066852.364      162579.044
     2066819.812      162802.568
#Sta/Elev= 30
       0 2140.97      98 2134.78   140.5 2130.71   176.5 2125.11     219 2116.79
   245.1 2109.33     268 2100.83   366.1 2059.95  397.592051.119  458.712041.435
   467.4  2038.1     487 2037.01  511.352031.241   522.9 2028.42     536 2026.78
  581.182025.747   648.5 2025.43   656.9 2023.45   666.7 2025.99   679.8 2030.77
     706  2036.2   715.8 2039.45   738.6 2049.99   751.7 2052.29   774.6  2067.2
   836.7 2093.93   915.3  2115.2   990.6 2139.52  1036.4 2147.97  1049.5 2151.38
#Mann= 7 ,-1 , 0
       0     .12       0  397.59     .06       0  458.71    .016       0
  511.35     .06       0  581.18     .12       0   648.5    .045       0
   666.7     .12       0
Bank Sta=648.5,666.7
XS Rating Curve= 0 ,0
Exp/Cntr=0.3,0.1

Type RM Length L Ch R = 1 ,61714.8 ,366.7,362.1,355.7
XS GIS Cut Line= 3
     2065946.309        162235.9     2066253.405      162294.755
     2066717.815      162815.589
#Sta/Elev= 30
       0 2219.05    48.9 2197.37    74.9 2187.49   143.3 2165.92   198.7 2152.43
   276.9 2127.32   312.7 2112.98     352 2101.09   368.4 2094.33   417.5  2077.3
   476.5 2053.91   515.8 2036.93   528.9  2030.5   555.1 2015.66  560.622015.013
  618.792014.487  667.382013.227   686.2 2012.73   696.2 2010.03   702.5 2008.82
   711.2 2009.87   715.6 2011.69   728.8 2024.94   738.6 2030.71   836.9 2071.64
   859.8 2082.55     922 2115.31   954.8 2131.42   987.6 2145.98  1010.5 2154.33
#Mann= 6 ,-1 , 0
       0     .12       0  560.62     .06       0  618.79    .016       0
  667.38     .12       0   696.2    .045       0   711.2     .12       0
#XS Ineff= 2 , 0
          629.51 2039.29
Permanent Ineff=
       F       F
Bank Sta=696.2,711.2
XS Rating Curve= 0 ,0
Exp/Cntr=0.3,0.1

Type RM Length L Ch R = 1 ,61352.7 ,182.3,211.8,239.7
XS GIS Cut Line= 2
     2065765.072      162416.491     2066574.586      163108.557
#Sta/Elev= 30
       0 2247.74    22.9 2231.93    88.5 2194.36   216.3 2126.83   298.2 2080.38
   324.4 2067.13   357.2 2054.47   376.8 2049.96   416.2 2036.11   465.3 2008.75
  495.022006.412  500.042006.499  548.242008.551   573.5 2009.29  625.822007.275
   642.3 2006.08  667.452006.435   678.3 2006.82     695 2005.01   704.6 2004.06
   711.1 2004.78   714.4 2006.32   724.2 2014.98   750.4 2021.08   763.5 2026.19
   799.6  2042.8     816 2051.97   897.9 2093.15   976.5 2135.77    1065  2191.3
#Mann= 8 ,-1 , 0
       0     .12       0  495.02     .06       0  500.04     .12       0
  548.24     .06       0  625.82    .016       0  667.45     .12       0
     695    .045       0   714.4     .12       0
#XS Ineff= 2 , 0
          564.39 2046.13
Permanent Ineff=
       F       F
Bank Sta=695,714.4
XS Rating Curve= 0 ,0
Exp/Cntr=0.3,0.1

Type RM Length L Ch R = 1 ,61140.9 ,121.1,113.4,111.3
XS GIS Cut Line= 4
     2065686.947      162498.957     2066155.749      162876.353
     2066077.624      163193.193     2066413.996      163388.505
#Sta/Elev= 30
       0 2250.18   153.7 2150.64   248.6 2099.64   336.9 2067.44   395.8 2043.78
   408.8 2038.03   444.8 2015.31   461.2 2008.59   487.4 2005.22  550.992005.875
  628.03 2004.87  708.092003.388   714.6 2001.16   722.6 2000.08   729.6 2000.74
  738.512003.527  768.942003.024  879.992003.142     938 2003.32   957.6 2007.39
  1032.8 2028.88  1058.9 2043.91  1114.5 2061.95  1166.8  2083.3    1206 2105.93
  1228.9 2116.38  1238.7 2118.74  1274.6    2140    1291 2145.97  1317.1 2164.54
#Mann= 9 ,-1 , 0
       0     .12       0  550.99     .06       0  628.03    .016       0
  708.09     .06       0   714.6    .045       0   729.6    .016       0
  738.51     .08       0  768.94     .06       0  879.99     .12       0
#XS Ineff= 2 , 0
                          747.09         2037.86
Permanent Ineff=
       F       F
Bank Sta=714.6,729.6
XS Rating Curve= 0 ,0
Exp/Cntr=0.3,0.1

Type RM Length L Ch R = 1 ,61027.5 ,302.8,281.3,253.7
XS GIS Cut Line= 4
     2065604.534      162544.321      2066019.03      162882.863
     2066038.562      163197.533     2066368.423      163421.057
#Sta/Elev= 30
       0 2253.72    94.6 2196.29   146.8  2161.9   182.7 2142.32   221.9 2127.04
   287.2 2096.72   313.3 2086.72     359 2073.99   476.4 2028.82   486.2 2023.89
   509.1 2006.87   522.1  2003.7  537.752003.638   638.72001.708   678.2 2001.43
   691.6 1998.75   704.2 1997.81   717.2 1999.71     727 2002.16  839.192001.189
  851.212001.283   882.12003.898   902.7 2004.73  1000.7 2034.54  1039.9 2043.81
    1115 2075.91  1150.9 2098.84  1173.8 2103.45  1190.1 2110.34  1248.9  2143.8
#Mann= 8 ,-1 , 0
       0     .12       0  537.75     .06       0   638.7     .12       0
   691.6    .045       0   717.2     .12       0  839.19     .08       0
  851.21    .016       0   882.1     .12       0
#XS Ineff= 2 , 0
          630.75 2030.83  789.82         2030.42
Permanent Ineff=
       F       F
Bank Sta=691.6,717.2
XS Rating Curve= 0 ,0
Exp/Cntr=0.3,0.1

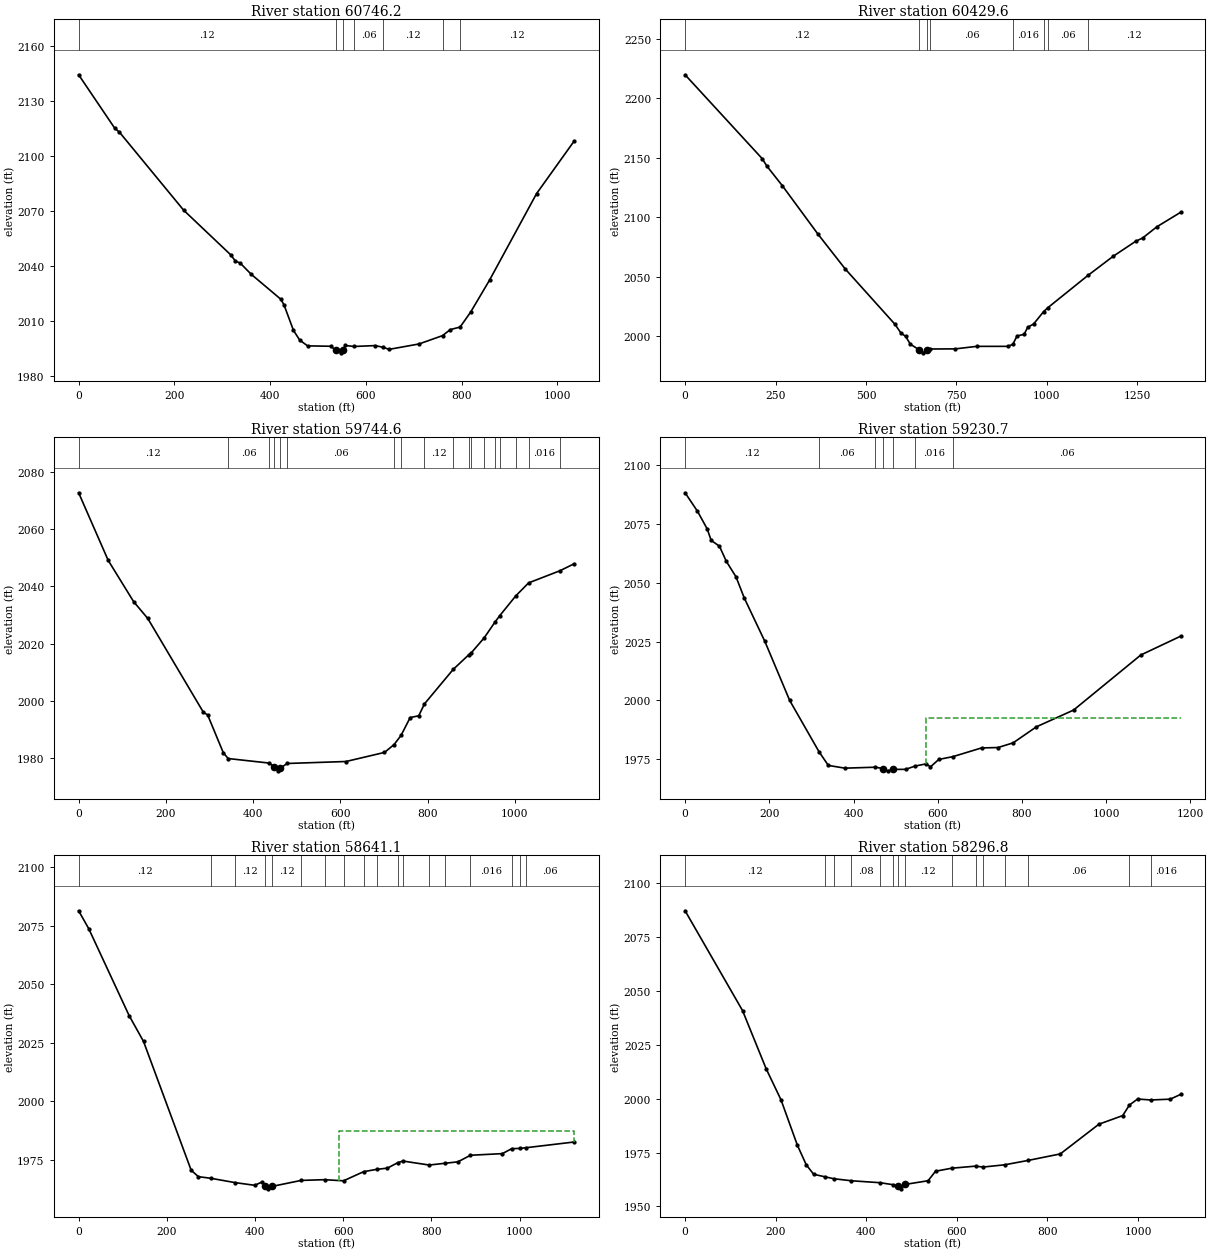
Type RM Length L Ch R = 1 ,60746.2 ,318.3,316.6,314.4
XS GIS Cut Line= 2
     2065409.221      162904.564     2066223.023      163544.755
#Sta/Elev= 30
       0 2144.19    75.4 2115.09    85.2 2112.94   219.5  2070.4   317.8  2046.1
   327.7 2042.63   337.5 2041.64   360.4 2035.55   422.7 2021.86   429.2 2018.78
   448.9 2004.93     462 1999.62   478.4 1996.51   527.6 1996.29   536.8    1994
   547.2 1992.71   551.8 1994.03     557 1996.73  575.38 1996.17   619.3 1996.66
  635.841995.763   648.8 1994.61     711 1997.53  760.292002.078   776.6 2005.38
  797.092006.762   819.2 2014.96   858.5 2032.28   956.8 2079.45  1035.4 2108.09
#Mann= 7 ,-1 , 0
       0     .12       0   536.8    .045       0   551.8     .12       0
  575.38     .06       0  635.84     .12       0  760.29    .016       0
  797.09     .12       0
Bank Sta=536.8,551.8
XS Rating Curve= 0 ,0
Exp/Cntr=0.3,0.1

Type RM Length L Ch R = 1 ,60429.6 ,684.9,685,685
XS GIS Cut Line= 2
     2065064.914      163104.003     2066210.437       163855.05
#Sta/Elev= 30
       0 2219.91     213 2149.45   226.1 2143.13   268.7 2126.72     367 2086.08
   442.4 2056.78     580 2010.24   596.4 2002.92   609.5 2000.06   622.6  1993.5
   646.4 1988.86   658.7 1986.19   668.5 1988.63  678.211989.422   747.2 1989.52
   806.1 1991.64   891.3 1991.64  905.731993.247   917.6 2000.35   937.2 2001.77
     947 2007.69   963.4 2010.44  990.792020.733 1002.432024.051 1113.562051.253
    1183 2067.28  1245.2 2079.87  1264.9 2082.76  1304.2 2092.16  1369.8 2104.32
#Mann= 8 ,-1 , 0
       0     .12       0   646.4    .045       0   668.5     .12       0
  678.21     .06       0  905.73    .016       0  990.79     .12       0
 1002.43     .06       0 1113.56     .12       0
Bank Sta=646.4,668.5
XS Rating Curve= 0 ,0
Exp/Cntr=0.3,0.1

Type RM Length L Ch R = 1 ,59744.6 ,505.9,513.9,524.2
XS GIS Cut Line= 3
     2064855.402      163716.196     2064949.152      163839.894
      2065768.57      164379.336
#Sta/Elev= 30
       0 2072.63    67.9    2049   126.1 2034.62   158.5 2028.76     286 1996.01
   295.8 1995.08   331.8 1981.85   342.91979.855  436.961978.271   447.7 1977.04
   456.1 1975.56   462.7  1976.5  477.961978.128     613 1978.82   701.3 1981.99
  723.271984.729  739.261987.928   760.2 1994.16   779.8 1994.78  792.991998.946
  858.962010.988  894.322016.042  900.442016.787  929.692021.952  954.172027.387
  965.05 2029.63 1002.272036.632  1031.82041.181 1103.452045.401  1136.2 2047.85
#Mann= 18 ,-1 , 0
       0     .12       0   342.9     .06       0  436.96     .12       0
   447.7    .045       0   462.7     .12       0  477.96     .06       0
  723.27     .12       0  739.26    .016       0  792.99     .12       0
  858.96    .016       0  894.32     .06       0  900.44    .016       0
  929.69     .06       0  954.17    .016       0  965.05     .08       0
 1002.27     .12       0  1031.8    .016       0 1103.45     .12       0
Bank Sta=447.7,462.7
XS Rating Curve= 0 ,0
Exp/Cntr=0.3,0.1

Type RM Length L Ch R = 1 ,59230.7 ,565.9,589.6,601.3
XS GIS Cut Line= 4
     2064673.544      164035.207     2064753.839      164217.498
     2065083.701      164599.443      2065554.57      164642.725
#Sta/Elev= 30
       0 2088.29    29.4 2080.43    52.2 2073.02      62 2068.05    81.6 2065.56
      98  2059.1   120.8 2052.59   140.4 2043.59   189.4  2025.1   248.4 1999.98
  317.921978.207   340.1 1972.37   379.4  1971.2  452.091971.604   470.8 1971.01
     481 1970.06   494.1 1970.68   523.6 1970.69  545.921972.081   572.8 1973.04
   582.6 1971.74   602.3  1974.9  636.341976.119   703.9  1979.8     743 1979.97
   778.9 1981.95   834.3 1988.79   922.4 1995.89  1082.1 2019.31  1176.7 2027.31
#Mann= 7 ,-1 , 0
       0     .12       0  317.92     .06       0  452.09     .12       0
   470.8    .045       0   494.1     .06       0  545.92    .016       0
  636.34     .06       0
#XS Ineff= 2 , 0
                          571.17         1992.67
Permanent Ineff=
       F       F
Bank Sta=470.8,494.1
XS Rating Curve= 0 ,0
Exp/Cntr=0.3,0.1

Type RM Length L Ch R = 1 ,58641.1 ,325.4,344.3,360.8
XS GIS Cut Line= 3
      2064606.27      164106.821     2064552.017      164890.241
     2064660.236      165210.932
#Sta/Elev= 30
       0 2081.41    22.9 2073.77   114.5 2036.64   147.2 2025.58   255.2 1970.57
   271.6 1967.83  299.971967.135  354.581965.296   399.2 1964.14   415.6 1965.52
   423.1 1963.98   428.6 1962.63   438.1 1963.65  504.481966.226  557.671966.542
  600.691966.063   646.51969.977  676.111970.952   700.2 1971.47  723.721973.803
  735.331974.506  795.041972.796  831.51 1973.56   860.2 1974.17  888.571976.976
     961 1977.67   982.11979.792 1001.651979.904 1014.591980.193  1123.8 1982.64
#Mann= 18 ,-1 , 0
       0     .12       0  299.97     .06       0  354.58     .12       0
   423.1    .045       0   438.1     .12       0  504.48     .08       0
  557.67     .06       0  600.69     .12       0   646.5     .06       0
  676.11    .016       0  723.72     .06       0  735.33     .12       0
  795.04     .06       0  831.51     .08       0  888.57    .016       0
   982.1     .08       0 1001.65     .12       0 1014.59     .06       0
#XS Ineff= 2 , 0
                          589.49          1987.5
Permanent Ineff=
       F       F
Bank Sta=423.1,438.1
XS Rating Curve= 0 ,0
Exp/Cntr=0.3,0.1

Type RM Length L Ch R = 1 ,58296.8 ,581.8,580.2,571.5
XS GIS Cut Line= 3
     2064561.999       164089.46     2064506.444      164238.766
     2063835.929      164890.063
#Sta/Elev= 30
       0 2087.18   126.8 2040.89     179 2013.87   211.8 1999.46   247.9 1978.42
   267.5 1969.35   283.9 1964.93  309.861963.727  328.721962.866  367.161961.937
  430.87 1961.03  458.971960.114   470.5 1959.54   477.4 1958.19   485.5 1960.23
   536.5 1961.95   552.9 1966.35  588.441967.758  641.191968.718  658.181968.305
   705.51969.336  756.721971.344   828.4 1974.39   913.7 1988.18   966.2 1992.17
  980.981997.052     999 1999.85 1028.381999.412  1071.1 1999.79  1094.1 2001.99
#Mann= 15 ,-1 , 0
       0     .12       0  309.86     .08       0  328.72     .06       0
  367.16     .08       0  430.87     .06       0  458.97     .12       0
   470.5    .045       0   485.5     .12       0  588.44     .06       0
  641.19     .12       0  658.18     .06       0   705.5    .016       0
  756.72     .06       0  980.98     .08       0 1028.38    .016       0
Bank Sta=470.5,485.5
XS Rating Curve= 0 ,0
Exp/Cntr=0.3,0.1

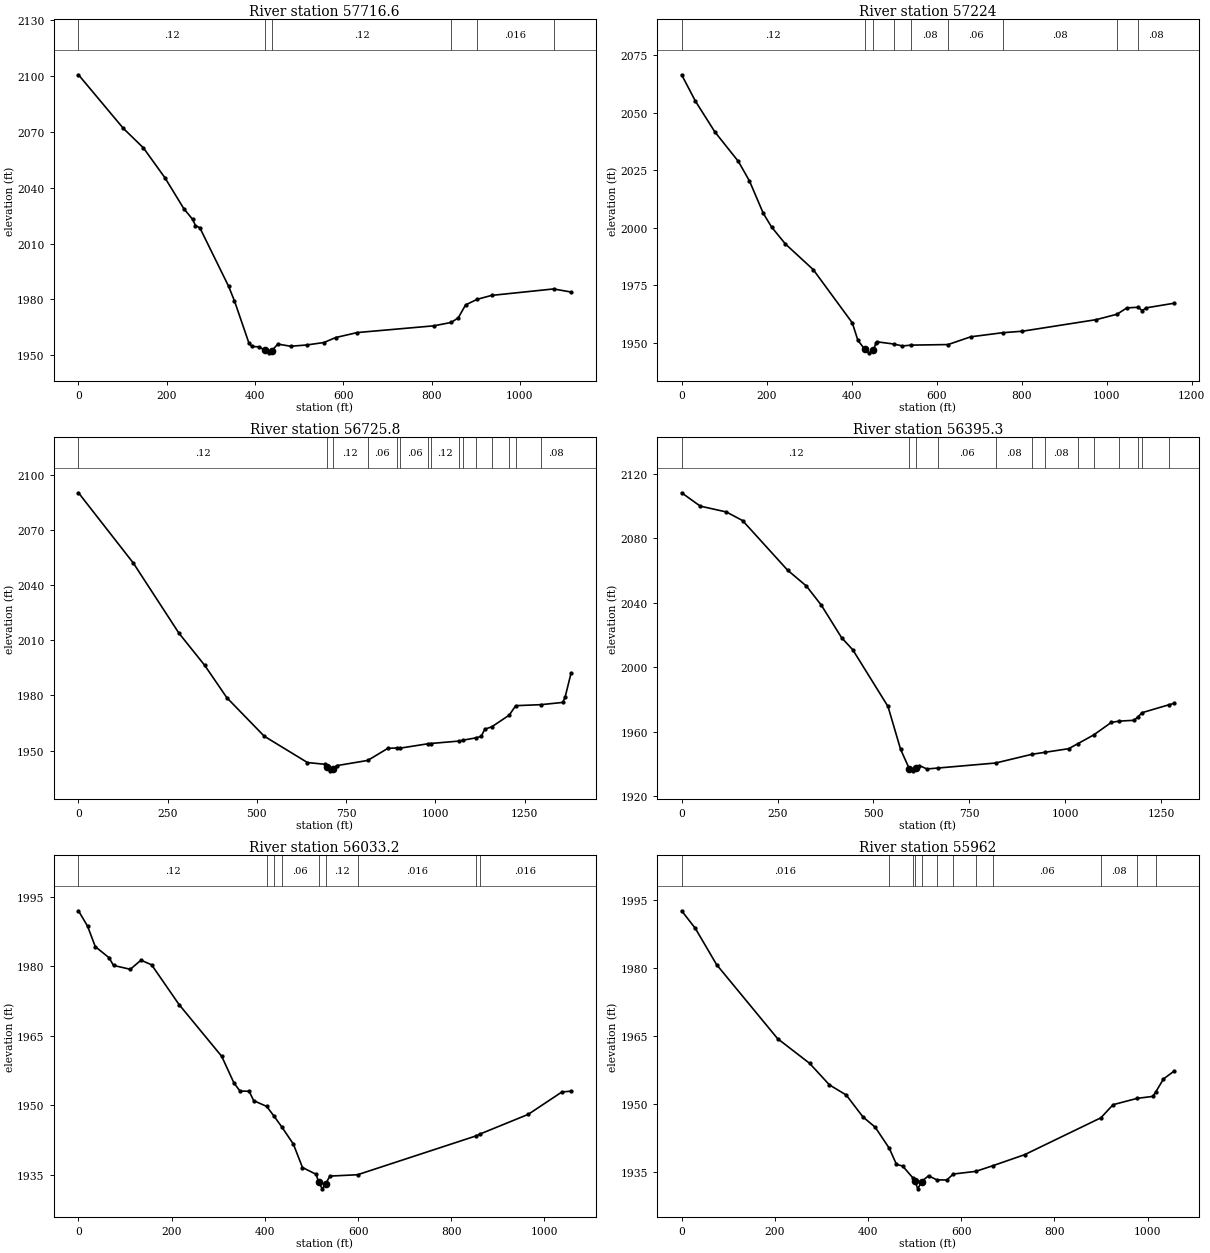
Type RM Length L Ch R = 1 ,57716.6 ,488.2,492.5,490.9
XS GIS Cut Line= 2
     2064154.013      163719.669     2063558.367      164663.482
#Sta/Elev= 30
       0 2100.78   101.5 2071.98   147.3 2061.41   196.4 2045.19   238.9 2028.68
   258.6 2023.02   265.1 2019.65   274.9 2018.51   340.4 1986.88   353.5 1979.07
   386.2 1956.44   392.8 1954.61   409.1 1954.41   422.9 1952.51     432 1951.19
   437.9 1952.33   451.7 1955.89   481.1 1954.73   517.1 1955.42   556.4 1956.75
   582.6 1959.41   631.7  1962.1   805.1 1965.72  844.791967.551   860.8 1970.12
   877.1 1976.98  903.571979.997     936 1982.09 1076.411985.562    1116 1983.91
#Mann= 6 ,-1 , 0
       0     .12       0   422.9    .045       0   437.9     .12       0
  844.79     .06       0  903.57    .016       0 1076.41     .08       0
Bank Sta=422.9,437.9
XS Rating Curve= 0 ,0
Exp/Cntr=0.3,0.1

Type RM Length L Ch R = 1 ,57224   ,496.9,498.2,499.4
XS GIS Cut Line= 3
      2063758.18      163396.752      2063664.43      163636.335
     2063204.676      164411.714
#Sta/Elev= 30
       0 2066.46    32.6 2054.95    78.2 2041.62   133.5  2028.8   159.6  2020.3
   192.1 2006.24   211.7 2000.27   244.2 1992.91   309.7 1981.76   401.5 1958.64
   414.6 1951.07     431  1947.1   440.8 1945.61   450.7  1946.7   457.2 1949.74
   460.5 1950.38  498.631949.447   519.5 1948.61  539.651948.963  626.76 1949.21
   680.1 1952.58  755.711954.368   801.4    1955   975.1 1960.03 1024.47  1962.4
  1047.3 1965.15 1074.411965.417  1083.3 1963.96  1093.2 1965.17  1158.7 1967.18
#Mann= 9 ,-1 , 0
       0     .12       0     431    .045       0   450.7     .12       0
  498.63     .06       0  539.65     .08       0  626.76     .06       0
  755.71     .08       0 1024.47    .016       0 1074.41     .08       0
Bank Sta=431,450.7
XS Rating Curve= 0 ,0
Exp/Cntr=0.3,0.1

Type RM Length L Ch R = 1 ,56725.8 ,331.4,330.5,328.4
XS GIS Cut Line= 3
     2063578.072      162963.245     2063189.388      163546.077
     2062786.637       164093.66
#Sta/Elev= 30
       0  2090.2   153.9 2051.93   281.5 2013.85   353.6  1996.4   415.8 1978.75
   520.5 1957.83   641.6  1943.5   690.7 1942.54   697.1 1940.91   703.8 1938.98
   712.1 1940.08   723.4  1941.8  810.511944.632   867.2 1951.24  891.591951.407
  902.271951.345  980.511953.738  987.081953.848 1067.341955.186 1077.791955.652
 1114.071956.932  1128.7 1957.74  1138.5  1961.6 1158.421962.945 1207.081969.258
 1225.341974.426 1295.881974.964  1357.4 1976.19    1364 1979.26  1380.3 1992.01
#Mann= 15 ,-1 , 0
       0     .12       0   697.1    .045       0   712.1     .12       0
  810.51     .06       0  891.59     .08       0  902.27     .06       0
  980.51     .08       0  987.08     .12       0 1067.34     .06       0
 1077.79     .12       0 1114.07    .016       0 1158.42     .08       0
 1207.08     .12       0 1225.34    .016       0 1295.88     .08       0
Bank Sta=697.1,712.1
XS Rating Curve= 0 ,0
Exp/Cntr=0.3,0.1

Type RM Length L Ch R = 1 ,56395.3 ,371.3,362.1,351.5
XS GIS Cut Line= 3
      2063329.36      162879.391     2063157.485       162995.71
     2062598.582      163916.014
#Sta/Elev= 30
       0 2108.19    48.6 2099.91   116.7 2096.29   158.9 2090.96   276.3  2060.2
   325.4 2050.35   364.6 2038.38     417 2018.38   446.4  2010.8   538.1 1975.69
   570.8 1949.22   593.7 1937.05   603.5 1935.79   611.8 1937.27   619.9 1939.08
   639.5 1936.95  669.481937.556  818.861940.644  914.121946.086  946.441947.233
  1009.4 1949.54 1033.731952.704  1074.71958.084  1120.6 1965.85 1141.461966.614
  1179.5 1967.13 1190.591969.347 1200.351971.826 1270.151976.723  1284.3 1977.62
#Mann= 13 ,-1 , 0
       0     .12       0   593.7    .045       0   611.8     .12       0
  669.48     .06       0  818.86     .08       0  914.12    .016       0
  946.44     .08       0 1033.73     .06       0  1074.7     .08       0
 1141.46    .016       0 1190.59     .08       0 1200.35     .06       0
 1270.15     .08       0
Bank Sta=593.7,611.8
XS Rating Curve= 0 ,0
Exp/Cntr=0.3,0.1

Type RM Length L Ch R = 1 ,56033.2 ,71,71.2,71.5
XS GIS Cut Line= 4
     2062950.888      162742.238     2062650.541      163079.044
     2062622.763      163303.002     2062419.638      163624.182
#Sta/Elev= 30
       0 1991.95    19.6 1988.61      36 1984.23    65.4 1981.84    75.2 1980.17
   111.2 1979.33   134.1  1981.3     157 1980.29   215.8 1971.74   307.4 1960.56
   333.6 1954.83   346.6 1953.08   366.2 1953.03   376.1    1951  403.85 1949.77
  419.441947.699  436.391945.329   461.1 1941.65   480.7 1936.59   510.1 1935.12
   515.3 1933.46   523.2 1931.99   530.3 1933.05   539.6 1934.74  598.811935.027
  853.171943.403  861.711943.809   965.2 1948.05  1037.3 1952.87    1057 1953.06
#Mann= 9 ,-1 , 0
       0     .12       0  403.85     .06       0  419.44     .12       0
  436.39     .06       0   515.3    .045       0   530.3     .12       0
  598.81    .016       0  853.17     .12       0  861.71    .016       0
Bank Sta=515.3,530.3
XS Rating Curve= 0 ,0
Exp/Cntr=0.3,0.1

Type RM Length L Ch R = 1 ,55962   ,225.2,240.3,253.6
XS GIS Cut Line= 4
     2062879.707       162745.71      2062579.36      163082.516
     2062551.582      163306.474     2062348.457      163627.655
#Sta/Elev= 30
       0 1992.64    29.4 1988.76    75.2 1980.75     206 1964.46   274.7 1959.02
   317.2 1954.27   353.2 1952.05   389.1 1947.22   415.3 1944.96  445.641940.305
   461.1 1936.74   474.2 1936.41   496.11933.801     500 1933.19   506.9 1931.37
     515 1932.98   529.8 1934.25  547.681933.345     569 1933.32  583.111934.633
  631.241935.221  667.491936.453   735.9 1938.89  899.721947.023   925.9 1949.91
  977.531951.304  1011.1 1951.74 1017.091952.642    1034 1955.58    1057 1957.32
#Mann= 12 ,-1 , 0
       0    .016       0  445.64     .06       0   496.1     .12       0
     500    .045       0     515     .12       0  547.68     .08       0
  583.11     .06       0  631.24     .08       0  667.49     .06       0
  899.72     .08       0  977.53    .016       0 1017.09     .08       0
Bank Sta=500,515
XS Rating Curve= 0 ,0
Exp/Cntr=0.3,0.1

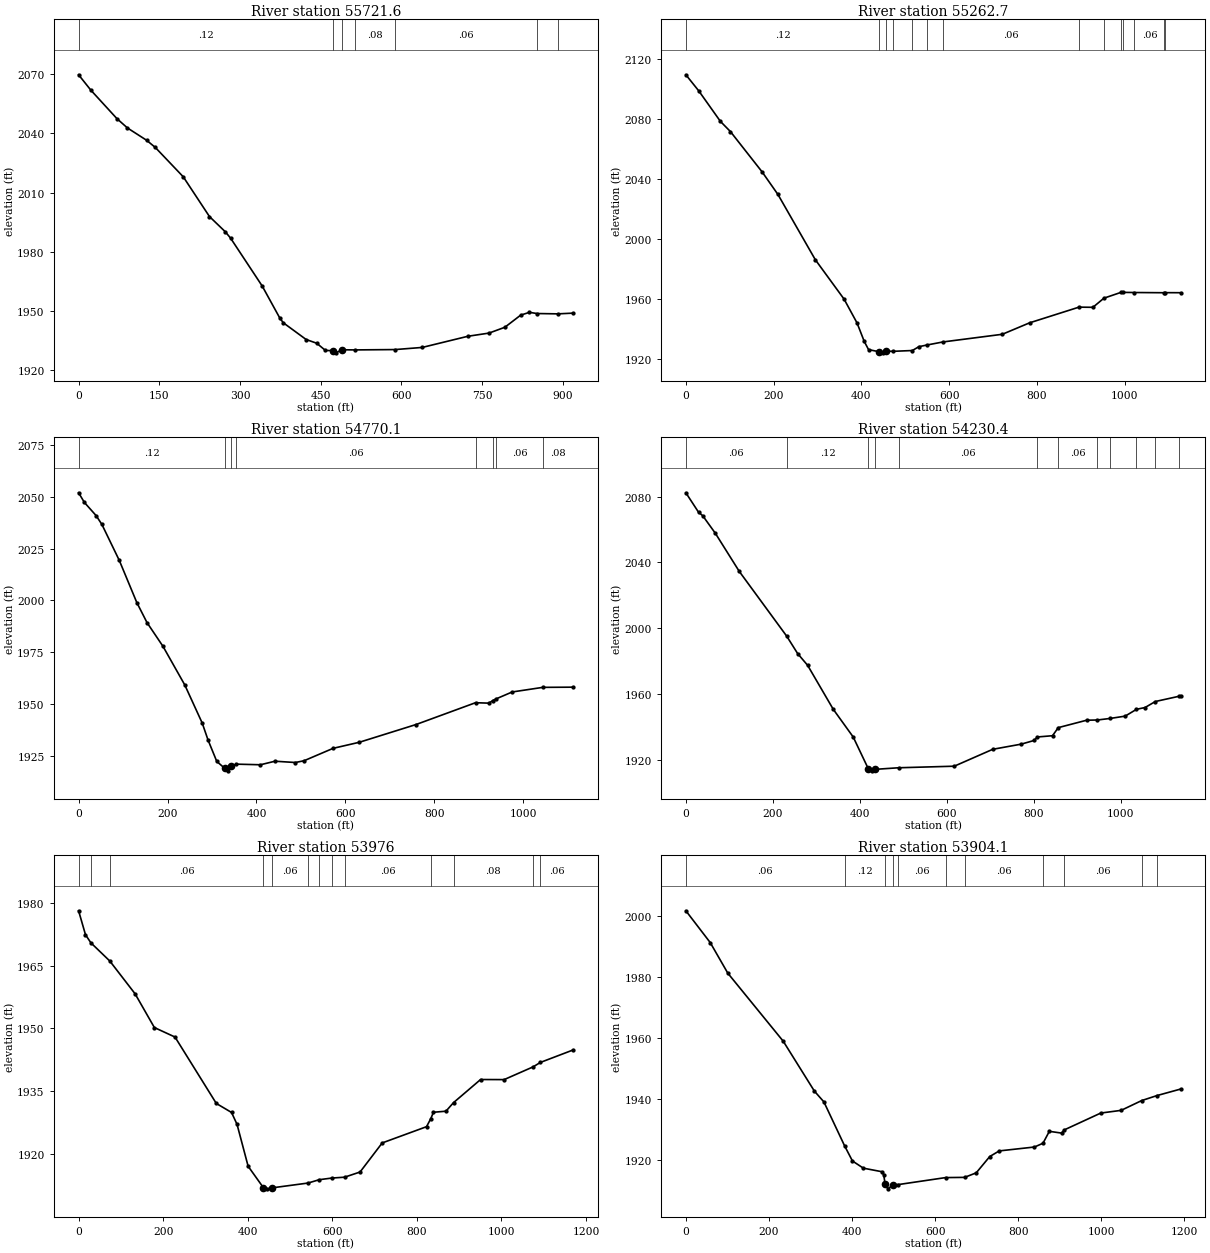
Type RM Length L Ch R = 1 ,55721.6 ,456.1,459,455.6
XS GIS Cut Line= 3
     2062615.819      162601.613      2062539.43      162825.571
     2062091.513      163341.196
#Sta/Elev= 30
       0 2069.78    22.7    2062    71.3 2047.52    90.8  2042.8   126.4 2036.56
   142.6 2032.91   194.5 2018.03   243.2 1997.87   272.6 1990.16   282.4 1986.94
   341.2 1962.64   373.9  1946.4   380.4 1943.99   422.9 1935.49   442.5 1933.61
   458.8 1929.94   471.9 1929.84   478.5 1928.73     489 1930.29  513.811930.215
  588.29 1930.39   638.6 1931.47   723.6 1937.14   762.8 1938.75   792.2  1941.7
   821.6 1947.85   837.9 1949.28  851.871948.671  890.741948.503   919.6 1948.88
#Mann= 7 ,-1 , 0
       0     .12       0   471.9    .045       0     489     .12       0
  513.81     .08       0  588.29     .06       0  851.87     .08       0
  890.74    .016       0
Bank Sta=471.9,489
XS Rating Curve= 0 ,0
Exp/Cntr=0.3,0.1

Type RM Length L Ch R = 1 ,55262.7 ,504.1,492.6,475
XS GIS Cut Line= 2
     2062371.027      162367.238     2061608.142      163197.603
#Sta/Elev= 30
       0 2109.29    29.5 2098.51    78.7 2078.22   101.6  2071.4   173.7 2044.55
   209.8 2029.48     295 1985.97   360.6 1959.67   390.1 1943.79   406.5 1931.49
   416.3 1926.03   440.6 1924.61   449.1 1923.88   455.6 1925.02  471.291924.884
  516.071925.425     531 1927.98  550.341929.154  586.221931.155   721.1 1936.25
   783.4  1943.9  895.841954.349   927.6 1954.24  952.72 1960.33  991.561964.195
  996.381964.201 1022.361964.101 1090.361963.956 1092.831964.009  1127.6 1963.97
#Mann= 14 ,-1 , 0
       0     .12       0   440.6    .045       0   455.6     .12       0
  471.29     .08       0  516.07     .06       0  550.34     .12       0
  586.22     .06       0  895.84    .016       0  952.72     .06       0
  991.56    .016       0  996.38     .08       0 1022.36     .06       0
 1090.36     .08       0 1092.83     .06       0
Bank Sta=440.6,455.6
XS Rating Curve= 0 ,0
Exp/Cntr=0.3,0.1

Type RM Length L Ch R = 1 ,54770.1 ,528,539.6,548.6
XS GIS Cut Line= 3
     2061759.482       162087.29      2061695.68      162974.877
     2061567.207      163157.169
#Sta/Elev= 30
       0 2051.91    13.1 2047.23    39.3 2040.93    52.4 2036.64    91.6 2019.26
   130.9 1998.98   153.8 1989.32   189.8 1977.84   238.8 1959.23   278.1 1940.81
   291.2 1932.63   310.8 1922.33   328.2  1919.1     337 1917.79   343.2    1920
  354.771921.018     409 1920.72   441.7 1922.43   487.5 1921.81   507.1 1922.66
   572.5 1928.65   631.4 1931.57     759 1940.13  892.781950.652   922.7 1950.44
  931.381951.654  938.981952.498   975.2 1955.83 1044.121958.055  1112.9 1958.15
#Mann= 8 ,-1 , 0
       0     .12       0   328.2    .045       0   343.2     .12       0
  354.77     .06       0  892.78    .016       0  931.38     .08       0
  938.98     .06       0 1044.12     .08       0
Bank Sta=328.2,343.2
XS Rating Curve= 0 ,0
Exp/Cntr=0.3,0.1

Type RM Length L Ch R = 1 ,54230.4 ,264.7,254.4,241.8
XS GIS Cut Line= 3
     2061553.319      161915.849     2061449.152      161980.953
     2060927.276       162851.95
#Sta/Elev= 30
       0 2082.29    29.1 2070.49    38.8 2068.33    67.9 2057.63   122.8  2034.5
  232.061995.075   257.1 1984.54   280.1 1977.38     339 1950.67   384.9 1933.82
   419.5 1914.58   427.4 1913.24   434.5 1914.13  489.191915.108   617.4 1916.06
   705.9 1926.33   771.4 1929.47   800.8 1931.69  808.691933.835   843.4 1934.59
  856.631939.509     922 1944.02  946.321944.145  976.661945.117  1010.5  1946.5
 1036.581950.642  1056.3 1951.74 1079.961955.392 1135.011958.608  1138.2 1958.84
#Mann= 12 ,-1 , 0
       0     .06       0  232.06     .12       0   419.5    .045       0
   434.5     .12       0  489.19     .06       0  808.69    .016       0
  856.63     .06       0  946.32     .08       0  976.66     .06       0
 1036.58    .016       0 1079.96     .12       0 1135.01     .08       0
Bank Sta=419.5,434.5
XS Rating Curve= 0 ,0
Exp/Cntr=0.3,0.1

Type RM Length L Ch R = 1 ,53976   ,73.6,71.9,71.8
XS GIS Cut Line= 4
      2061258.18      161722.707     2061084.569      161998.314
     2061058.527      162304.304     2060734.133      162732.593
#Sta/Elev= 30
       0 1978.12    16.3  1972.4   29.141970.456    73.81966.115   133.6 1958.28
   179.2 1950.22     228 1947.95   325.7 1932.08   361.7 1929.93   374.7 1927.08
   400.9 1917.08   436.8 1911.99   446.6 1911.68   456.4  1911.9  542.551913.063
  569.041913.862  598.681914.256  628.891914.462   665.6  1915.7     718 1922.65
   822.8 1926.53  832.851928.448   839.2 1929.98   868.7 1930.23  886.581932.275
   950.6  1937.8  1006.3 1937.78 1074.541940.812 1092.091941.886  1170.1 1944.89
#Mann= 13 ,-1 , 0
       0     .06       0   29.14     .12       0    73.8     .06       0
   436.8    .045       0   456.4     .06       0  542.55    .016       0
  569.04     .06       0  598.68     .08       0  628.89     .06       0
  832.85    .016       0  886.58     .08       0 1074.54     .12       0
 1092.09     .06       0
Bank Sta=436.8,456.4
XS Rating Curve= 0 ,0
Exp/Cntr=0.3,0.1

Type RM Length L Ch R = 1 ,53904.1 ,247.5,258.6,270.5
XS GIS Cut Line= 4
     2061180.055      161659.773     2061006.444       161935.38
     2061006.444      162308.644     2060706.964      162699.269
#Sta/Elev= 30
       0 2001.66    58.6 1991.23     101 1981.17   234.5 1958.82   309.4 1942.46
   332.3 1938.92  382.081924.504     401 1919.53   427.2 1917.17   473.1 1915.97
   476.4 1914.97   479.6 1911.94   486.2 1910.38   498.9 1911.69  511.671911.786
  625.271914.072  671.071914.144     699 1915.63   731.6 1920.99   754.4 1922.83
   839.2 1924.11  859.781925.352     875 1929.26   904.4 1928.68  911.191929.745
   998.9 1935.26  1047.8 1936.14 1097.291939.354 1134.511941.013  1191.2 1943.14
#Mann= 11 ,-1 , 0
       0     .06       0  382.08     .12       0   479.6    .045       0
   498.9     .12       0  511.67     .06       0  625.27    .016       0
  671.07     .06       0  859.78    .016       0  911.19     .06       0
 1097.29     .12       0 1134.51     .06       0
Bank Sta=479.6,498.9
XS Rating Curve= 0 ,0
Exp/Cntr=0.3,0.1

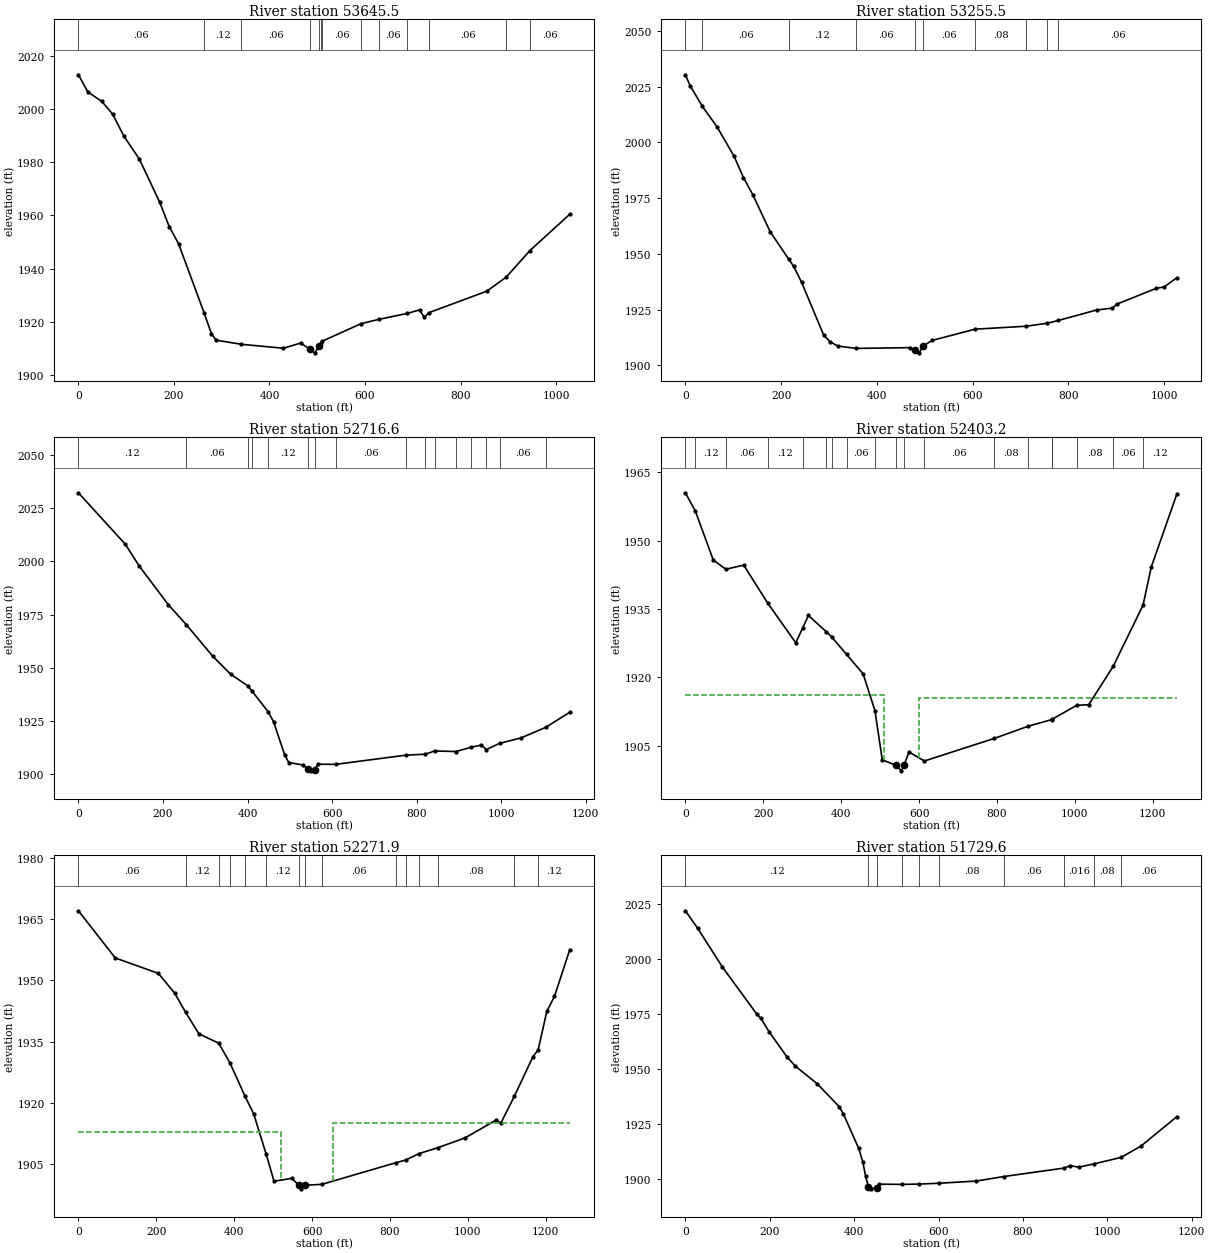
Type RM Length L Ch R = 1 ,53645.5 ,380.3,390,395.1
XS GIS Cut Line= 2
     2061019.464      161690.155      2060481.27      162566.891
#Sta/Elev= 30
       0 2013.06    19.7 2006.61    49.1 2002.99    72.1 1998.11      95 1989.98
   127.8 1981.19   170.4  1964.9     190 1955.84   209.7 1949.35  263.241923.228
   278.5 1915.38   288.3 1912.99  340.781911.428   429.2 1909.94   465.2 1911.88
   484.9 1909.55   494.7  1908.2   504.5 1910.68  507.821911.975  509.971912.549
  591.89 1919.21  628.911920.817  688.821923.087   714.2  1924.4     724 1921.61
  734.011923.363   855.1 1931.46  895.851936.776  945.351946.776  1028.8 1960.48
#Mann= 13 ,-1 , 0
       0     .06       0  263.24     .12       0  340.78     .06       0
   484.9    .045       0   504.5     .06       0  507.82     .08       0
  509.97     .06       0  591.89     .12       0  628.91     .06       0
  688.82    .016       0  734.01     .06       0  895.85     .08       0
  945.35     .06       0
Bank Sta=484.9,504.5
XS Rating Curve= 0 ,0
Exp/Cntr=0.3,0.1

Type RM Length L Ch R = 1 ,53255.5 ,538.4,538.9,532.1
XS GIS Cut Line= 2
     2060824.152      161553.436     2060066.773       162245.71
#Sta/Elev= 30
       0  2030.3     9.8 2025.44   35.232016.213    65.6  2007.1   101.6 1993.81
   121.3 1984.22     141 1976.43     177 1959.96  215.561947.724   226.2 1944.37
   242.6 1937.31   288.5 1913.75   301.6 1910.73     318 1908.71  356.731907.647
   468.8 1907.98   478.6 1907.12   488.5 1905.66   496.2 1908.66   514.7  1911.2
  604.911916.267  712.181917.596  755.971918.943  778.461920.163   858.9 1924.87
   891.7 1925.72   901.5 1927.53   983.5 1934.59   999.9 1935.22  1026.1  1939.3
#Mann= 10 ,-1 , 0
       0     .12       0   35.23     .06       0  215.56     .12       0
  356.73     .06       0   478.6    .045       0   496.2     .06       0
  604.91     .08       0  712.18    .016       0  755.97     .08       0
  778.46     .06       0
Bank Sta=478.6,496.2
XS Rating Curve= 0 ,0
Exp/Cntr=0.3,0.1

Type RM Length L Ch R = 1 ,52716.6 ,312.8,313.5,313.6
XS GIS Cut Line= 3
     2060661.392      161266.978     2060335.871      161340.762
      2059858.44      162017.846
#Sta/Elev= 30
       0 2032.39   111.3 2008.04     144  1997.8   212.7 1979.62  255.451970.136
   317.4  1955.4     360 1946.86  400.521941.369  411.34 1938.71  448.561929.177
   461.5 1924.52   487.7 1908.92   497.5 1905.19   530.3  1904.1   543.9 1901.99
   549.9 1901.29   558.9 1901.79   566.3  1904.4  609.441904.366  774.581908.684
  820.481909.127  842.341910.652  892.761910.396   928.91912.395   952.7 1913.45
  965.051911.338  996.131914.231  1047.6 1916.85 1105.691921.823  1162.3 1928.94
#Mann= 16 ,-1 , 0
       0     .12       0  255.45     .06       0  400.52     .12       0
  411.34     .06       0  448.56     .12       0   543.9    .045       0
   558.9     .12       0  609.44     .06       0  774.58     .12       0
  820.48     .08       0  842.34    .016       0  892.76     .06       0
   928.9    .016       0  965.05     .08       0  996.13     .06       0
 1105.69     .08       0
Bank Sta=543.9,558.9
XS Rating Curve= 0 ,0
Exp/Cntr=0.3,0.1

Type RM Length L Ch R = 1 ,52403.2 ,130.9,131.2,130.7
XS GIS Cut Line= 3
     2060411.826      161110.728     2060055.923      161279.998
     2059518.746      161961.001
#Sta/Elev= 30
       0 1960.52   25.751956.479    71.7 1945.74     1041943.753   149.8 1944.65
  211.06 1936.35   283.4 1927.61  301.091930.856   315.9  1933.6  361.261930.072
  375.891928.867  413.761925.057   456.3  1920.8  486.631912.736   505.4 1901.94
   541.4  1900.7   554.5 1899.52     561 1900.72   574.1 1903.64  613.63 1901.68
  793.111906.636  879.621909.294  940.181910.763  940.611910.785 1004.351913.884
  1035.6 1914.04 1098.141922.429 1174.891935.843    1196 1944.22  1261.5 1960.18
#Mann= 19 ,-1 , 0
       0     .06       0   25.75     .12       0     104     .06       0
  211.06     .12       0  301.09    .016       0  361.26     .06       0
  375.89     .12       0  413.76     .06       0  486.63     .12       0
   541.4    .045       0     561     .12       0  613.63     .06       0
  793.11     .08       0  879.62    .016       0  940.18     .08       0
  940.61     .06       0 1004.35     .08       0 1098.14     .06       0
 1174.89     .12       0
#XS Ineff= 2 , 0
          509.67  1916.1   599.1         1915.52
Permanent Ineff=
       F       F
Bank Sta=541.4,561
XS Rating Curve= 0 ,0
Exp/Cntr=0.3,0.1

Type RM Length L Ch R = 1 ,52271.9 ,528.5,542.3,527.7
XS GIS Cut Line= 3
     2060305.489      161041.283     2059949.586      161210.554
     2059412.409      161891.557
#Sta/Elev= 30
       0 1967.07    94.5 1955.51   205.2 1951.73   247.5 1946.84  275.251942.169
   309.4  1936.9  360.111934.627  388.981929.808  426.951921.775   449.8 1917.34
  482.031907.414   502.1 1900.79   547.9  1901.5   565.6 1899.82   570.8 1898.92
   580.6 1899.78  625.131900.025  815.921905.347  840.781906.004  874.081907.549
  922.37 1908.99   993.1 1911.43  1071.6 1915.73  1084.7 1915.05 1119.111921.607
  1166.6 1931.24 1180.36 1933.02  1202.6 1942.44  1222.2  1946.1  1261.5 1957.55
#Mann= 15 ,-1 , 0
       0     .06       0  275.25     .12       0  360.11     .06       0
  388.98     .12       0  426.95     .06       0  482.03     .12       0
   565.6    .045       0   580.6     .12       0  625.13     .06       0
  815.92     .08       0  840.78     .06       0  874.08    .016       0
  922.37     .08       0 1119.11     .06       0 1180.36     .12       0
#XS Ineff= 2 , 0
          520.75 1912.95   653.7         1915.14
Permanent Ineff=
       F       F
Bank Sta=565.6,580.6
XS Rating Curve= 0 ,0
Exp/Cntr=0.3,0.1

Type RM Length L Ch R = 1 ,51729.6 ,503.6,511.5,509
XS GIS Cut Line= 3
     2059969.117      160874.182     2059654.447      160900.224
     2059121.429      161560.804
#Sta/Elev= 30
       0 2021.71    29.3  2013.7    87.9  1996.1   169.3 1974.72     179 1972.79
   198.6 1966.67   240.9 1955.27   260.4 1951.15   312.5 1943.07   364.9 1932.61
   374.7 1929.27   410.8  1913.7   420.6  1907.5   427.2    1901   433.7 1896.39
   440.3 1895.33   453.5 1895.93   459.9 1897.46  513.421897.349  554.131897.495
  601.921897.876   689.4 1898.87  754.371900.916  897.641904.768   912.2 1905.88
   931.9 1905.17  967.361906.627  1032.8 1909.63  1079.4 1914.71  1164.6  1928.1
#Mann= 10 ,-1 , 0
       0     .12       0   433.7    .045       0   453.5     .12       0
  513.42     .08       0  554.13     .06       0  601.92     .08       0
  754.37     .06       0  897.64    .016       0  967.36     .08       0
  1032.8     .06       0
Bank Sta=433.7,453.5
XS Rating Curve= 0 ,0
Exp/Cntr=0.3,0.1