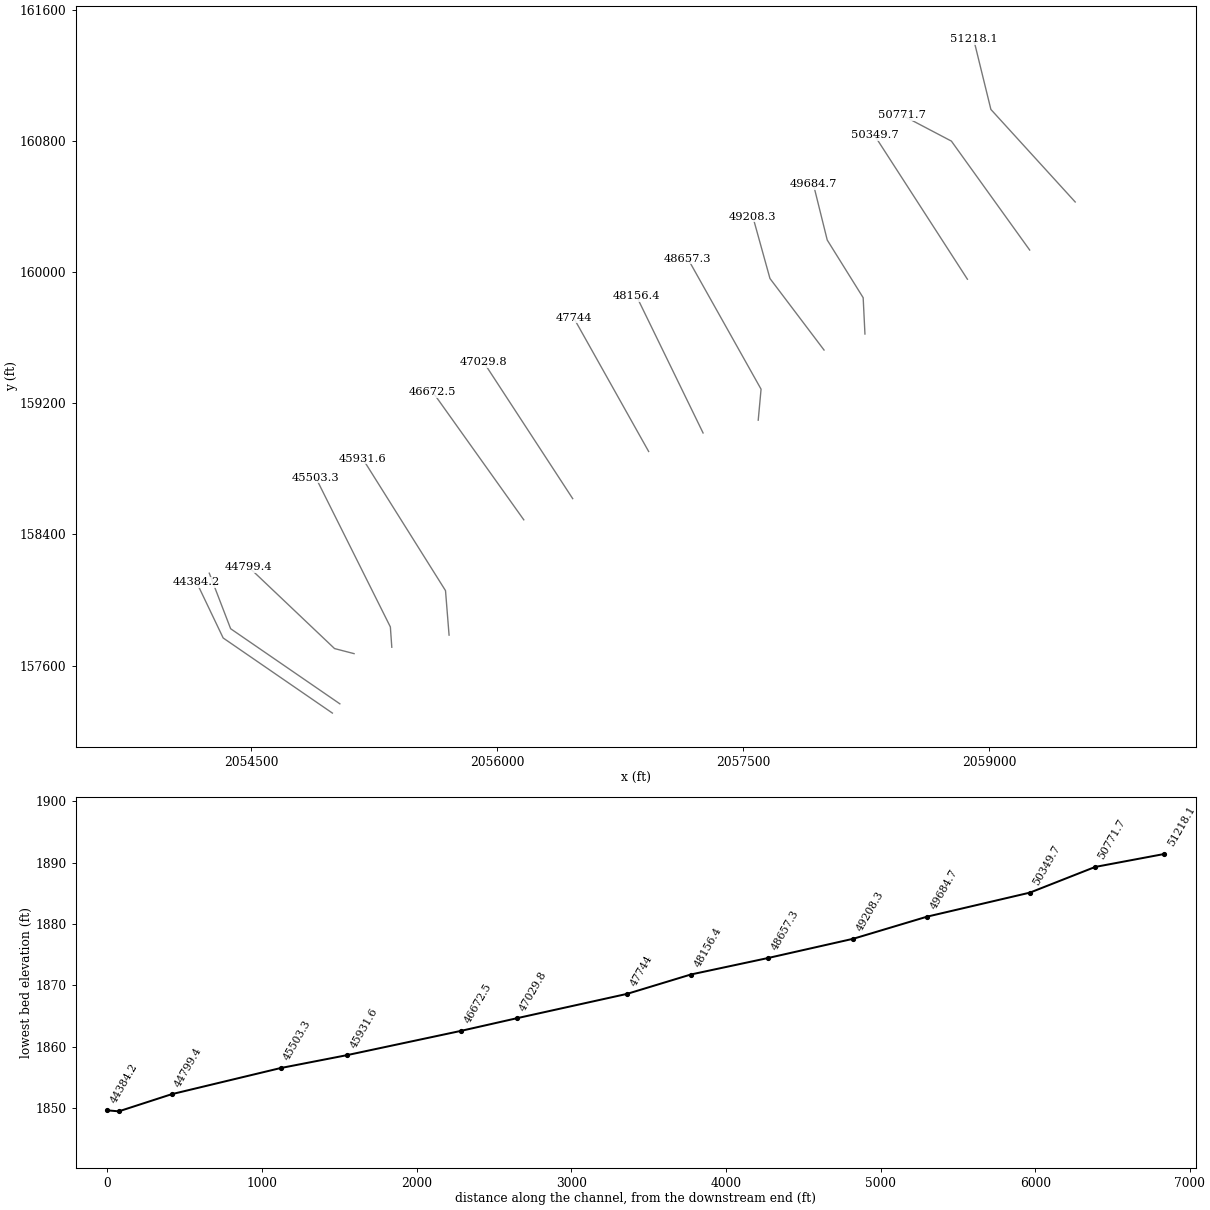
HEC-RAS study RICHCK.prj: RICHCK

--- RICHCK.g01 (geometry) --- (continued)

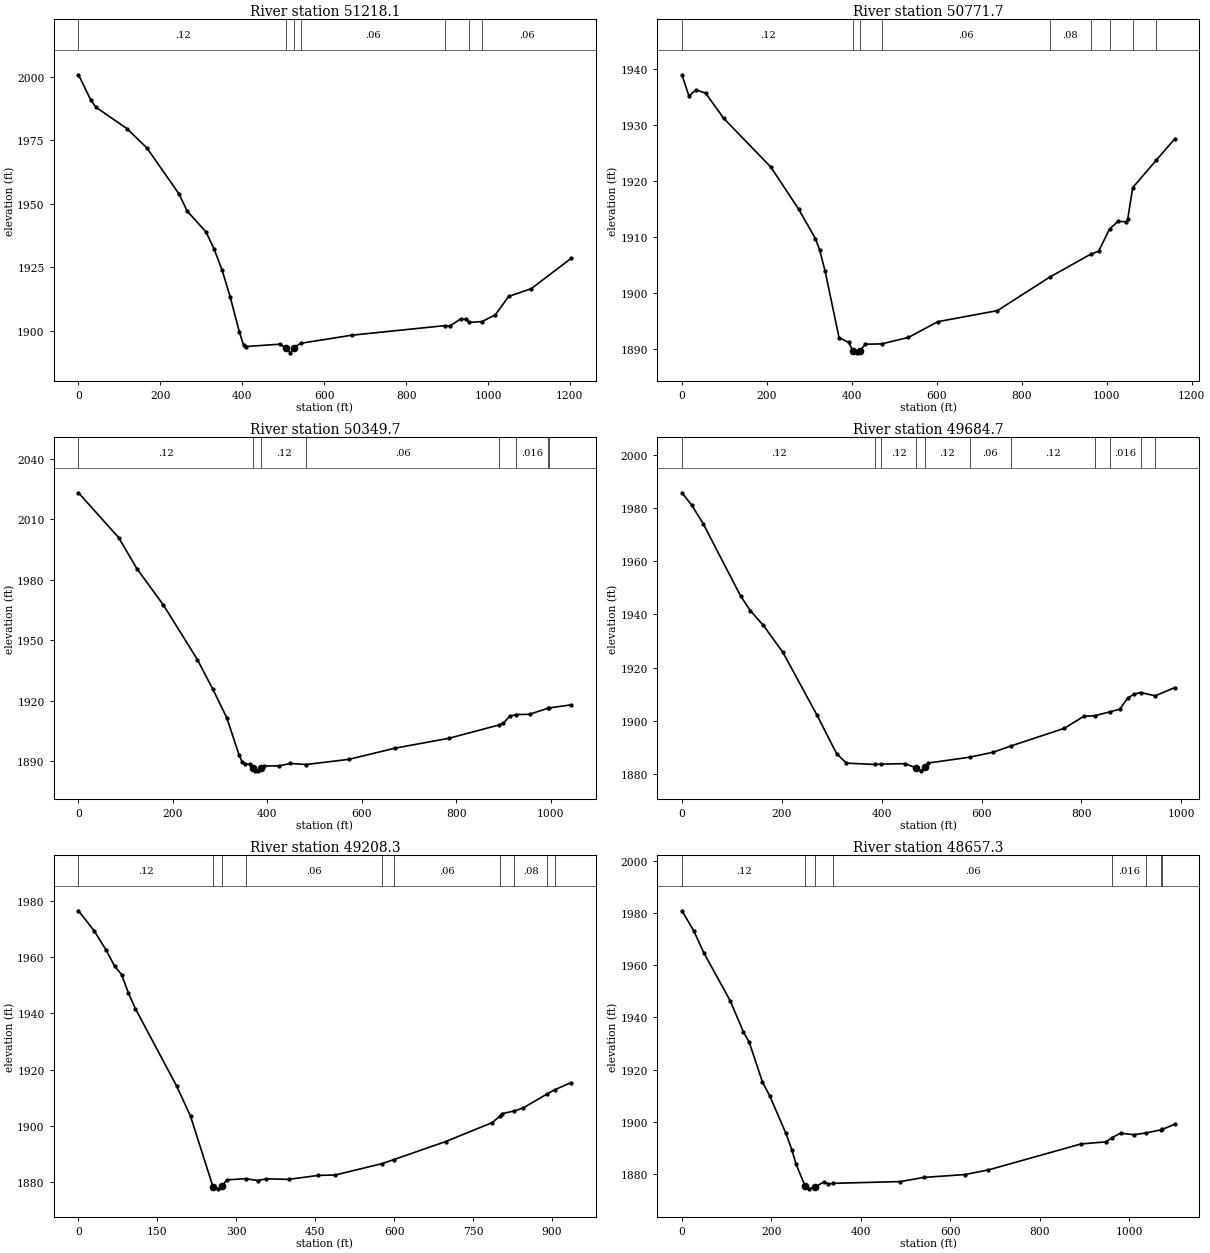
Type RM Length L Ch R = 1 ,51218.1 ,448.4,446.4,442.4
XS GIS Cut Line= 3
     2059526.409      160427.134     2059012.086       160991.37
     2058907.119      161418.833
#Sta/Elev= 30
       0 2000.75    29.5 1990.99    42.6 1987.99     118 1979.62   167.1 1971.98
   245.8 1953.82   265.4 1947.14   311.3 1938.98     331 1932.31   350.6    1924
   370.3 1913.48   393.2 1899.44     403 1894.52   409.6  1893.9   491.5 1894.81
   507.9 1893.19   517.7 1891.41   525.3 1893.46  543.091895.172   668.4 1898.37
  895.56 1902.12   906.9 1901.92     933 1904.73   946.1 1904.54  954.841903.383
  985.25  1903.7  1017.8  1906.3  1050.4  1913.6  1105.8 1916.64  1203.6 1928.63
#Mann= 7 ,-1 , 0
       0     .12       0   507.9    .045       0   525.3     .12       0
  543.09     .06       0  895.56    .016       0  954.84     .08       0
  985.25     .06       0
Bank Sta=507.9,525.3
XS Rating Curve= 0 ,0
Exp/Cntr=0.3,0.1

Type RM Length L Ch R = 1 ,50771.7 ,421.6,422,418.2
XS GIS Cut Line= 3
     2059248.631      160134.165     2058771.201      160798.228
     2058468.052      160957.358
#Sta/Elev= 30
       0 1938.96    16.4 1935.16    32.7 1936.27    55.6 1935.68    98.1 1931.19
   209.4 1922.46   274.8 1914.95   314.1  1909.7   323.9 1907.72     337 1903.88
   369.7 1892.03   392.6 1891.15   402.4 1889.68   412.2  1889.3   419.3 1889.69
   431.8 1890.84  469.991890.897   533.2 1892.05     602 1894.86   742.6 1896.84
  865.681902.822  962.411906.925   980.9 1907.46 1006.731911.432  1026.6 1912.79
  1046.1  1912.7  1049.4 1913.24 1061.231918.816 1116.481923.696  1160.2 1927.53
#Mann= 9 ,-1 , 0
       0     .12       0   402.4    .045       0   419.3     .12       0
  469.99     .06       0  865.68     .08       0  962.41     .06       0
 1006.73    .016       0 1061.23     .06       0 1116.48     .08       0
Bank Sta=402.4,419.3
XS Rating Curve= 0 ,0
Exp/Cntr=0.3,0.1

Type RM Length L Ch R = 1 ,50349.7 ,659.4,665,662.6
XS GIS Cut Line= 2
     2058868.857      159956.214     2058302.451       160832.95
#Sta/Elev= 30
       0 2023.18    85.1 2000.91   124.3 1985.29     180  1967.4     252 1940.29
   284.7 1925.55   314.1 1911.42   340.3 1892.87   346.8 1889.51   353.4 1888.43
   363.2  1888.4   368.8 1886.56     373 1885.11   379.6 1885.23   386.1 1886.64
   392.6 1887.49   425.4 1887.59   448.3 1888.78  482.021888.249   572.6 1890.82
   670.8 1896.39   785.3 1901.32  890.921907.905   899.8 1908.81   912.9 1912.11
  926.081913.065   955.4 1913.18  993.791916.187  996.421916.339  1043.8 1917.88
#Mann= 8 ,-1 , 0
       0     .12       0   368.8    .045       0   386.1     .12       0
  482.02     .06       0  890.92     .08       0  926.08    .016       0
  993.79     .12       0  996.42    .016       0
Bank Sta=368.8,386.1
XS Rating Curve= 0 ,0
Exp/Cntr=0.3,0.1

Type RM Length L Ch R = 1 ,49684.7 ,471.8,476.4,471.2
XS GIS Cut Line= 4
     2058243.857      159622.012     2058233.006      159843.366
     2058013.822      160194.929     2057929.187      160535.641
#Sta/Elev= 30
       0 1985.78    19.6  1981.1    42.4 1974.18   117.3    1947   136.9 1941.43
     163  1935.9   202.1 1925.76   270.6 1902.08   309.7 1887.66   329.3 1884.09
  386.371883.585  398.981883.719   446.7 1883.89   469.6 1882.24   479.3 1881.19
   485.8 1882.45   492.4  1884.1  576.721886.338   622.9 1888.18  658.251890.504
   765.9 1897.21   804.9 1901.72  826.191901.903  856.621903.354   876.5 1904.36
   892.7 1908.55   905.7  1910.1  918.961910.637  947.931909.407     987 1912.52
#Mann= 11 ,-1 , 0
       0     .12       0  386.37     .06       0  398.98     .12       0
   469.6    .045       0   485.8     .12       0  576.72     .06       0
  658.25     .12       0  826.19     .08       0  856.62    .016       0
  918.96     .08       0  947.93     .06       0
Bank Sta=469.6,485.8
XS Rating Curve= 0 ,0
Exp/Cntr=0.3,0.1

Type RM Length L Ch R = 1 ,49208.3 ,551.2,550.9,551
XS GIS Cut Line= 3
     2057994.291      159524.356      2057664.43      159960.554
     2057560.263      160335.988
#Sta/Elev= 30
       0 1976.55    29.5  1969.5    52.4  1962.6    68.8 1956.78    81.9 1953.87
      95 1947.22   108.1 1941.73   186.7 1914.08   212.9 1903.42   255.4 1878.42
   265.2 1877.59   273.4 1878.63   281.6 1880.78  317.441881.211   340.6 1880.55
     357 1881.15   399.5 1880.96   455.2 1882.37   487.9 1882.52  576.441886.542
  599.091887.987   697.5  1894.4   785.9 1901.14  800.56 1903.38   805.5 1904.38
  828.451905.331   844.8 1906.35  889.761911.285  904.741912.846   936.5 1915.42
#Mann= 10 ,-1 , 0
       0     .12       0   255.4    .045       0   273.4     .12       0
  317.44     .06       0  576.44     .08       0  599.09     .06       0
  800.56    .016       0  828.45     .08       0  889.76     .06       0
  904.74     .08       0
Bank Sta=255.4,273.4
XS Rating Curve= 0 ,0
Exp/Cntr=0.3,0.1

Type RM Length L Ch R = 1 ,48657.3 ,499,500.9,496
XS GIS Cut Line= 3
     2057592.815      159096.839     2057610.176      159285.641
     2057163.661      160080.913
#Sta/Elev= 30
       0 1980.81    26.2 1973.18      49 1964.69   107.9 1946.34   137.3 1934.47
   150.4  1930.5   179.8 1915.31   196.2 1910.01   232.2  1895.7   245.4 1889.46
   255.2 1883.79   274.9 1875.64   284.7 1874.45     298  1875.2   317.6 1877.13
   327.4 1876.31  337.971876.556   488.2 1877.23   540.6 1878.82   632.5 1879.91
     685 1881.69   891.7 1891.61   947.4 1892.41   961.71894.057   980.3 1895.74
  1009.8 1895.16 1038.231895.844 1071.171897.055 1073.211897.161  1101.6 1899.16
#Mann= 8 ,-1 , 0
       0     .12       0   274.9    .045       0     298     .12       0
  337.97     .06       0   961.7    .016       0 1038.23     .06       0
 1071.17    .016       0 1073.21     .06       0
Bank Sta=274.9,298
XS Rating Curve= 0 ,0
Exp/Cntr=0.3,0.1

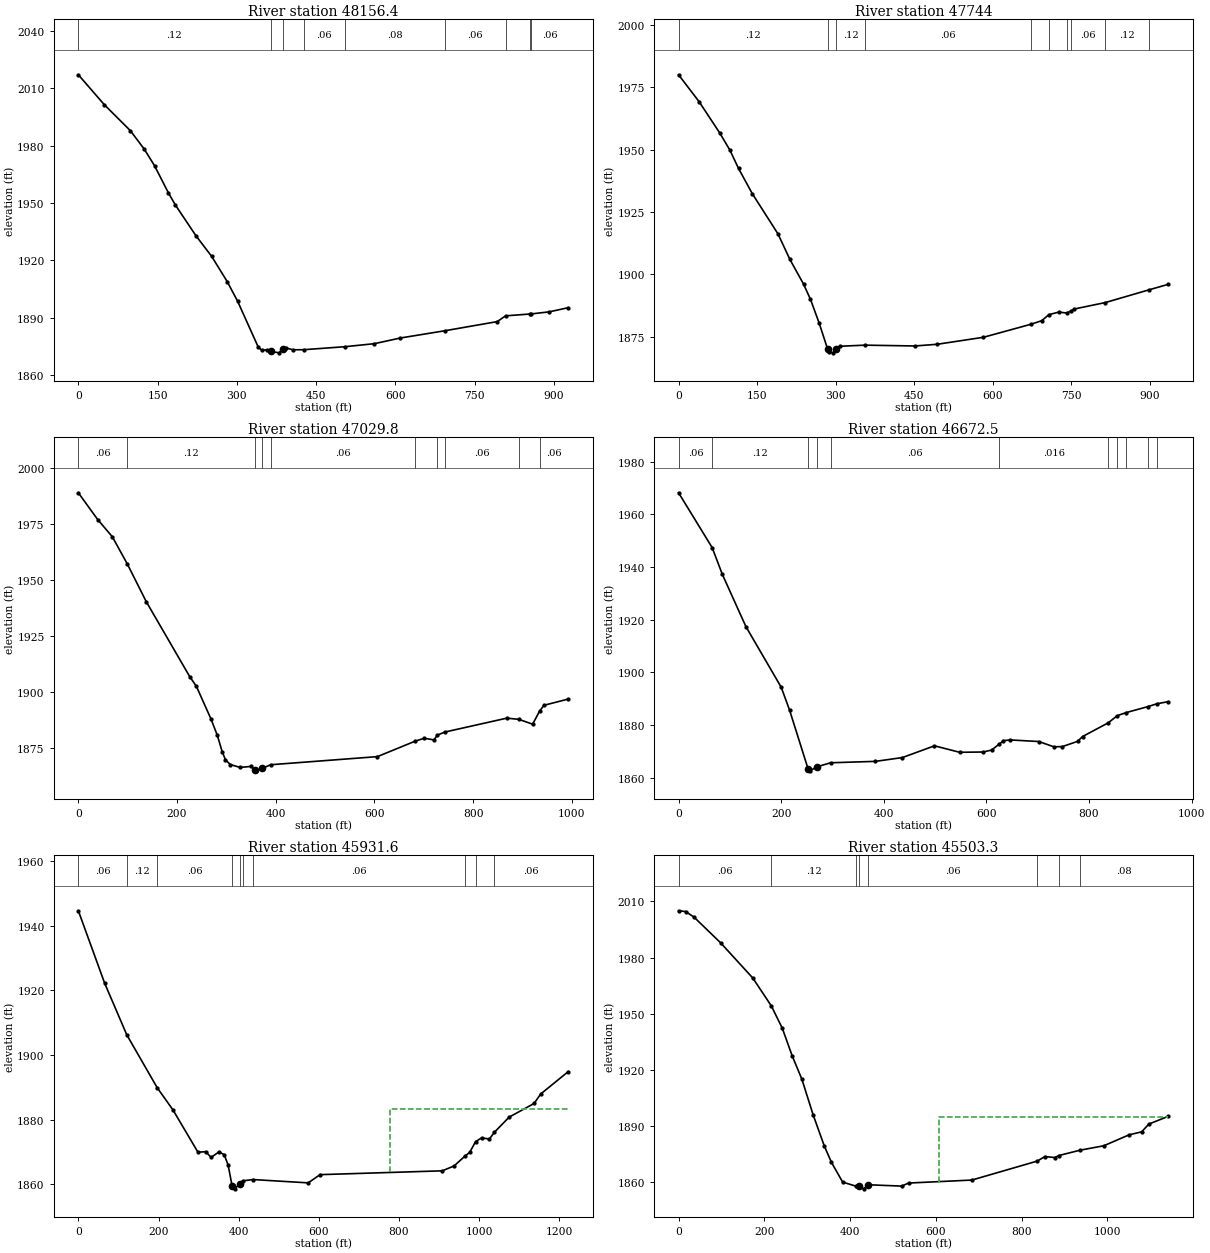
Type RM Length L Ch R = 1 ,48156.4 ,409.4,412.4,411.4
XS GIS Cut Line= 2
     2057256.444      159018.714     2056850.628      159852.047
#Sta/Elev= 30
       0 2016.94    49.1 2001.33    98.3  1987.8   124.5  1978.2   144.1  1969.5
   170.3 1955.33   183.4 1949.03   222.7 1932.82   252.2 1922.14   281.7 1908.94
   301.3 1898.74   340.6 1874.63   347.2 1873.13     357 1873.33   363.6 1872.55
   379.9 1871.75   386.3 1873.68     393 1874.31   406.1 1873.34  426.441873.388
  504.311874.947   560.1 1876.53   609.2 1879.49     6931883.258   792.6 1888.06
  808.36 1891.07  854.77 1892.03  856.491892.061   890.9 1893.15   926.9 1895.32
#Mann= 9 ,-1 , 0
       0     .12       0   363.6    .045       0   386.3     .12       0
  426.44     .06       0  504.31     .08       0     693     .06       0
  808.36    .016       0  854.77     .08       0  856.49     .06       0
Bank Sta=363.6,386.3
XS Rating Curve= 0 ,0
Exp/Cntr=0.3,0.1

Type RM Length L Ch R = 1 ,47744   ,647,714.2,705.4
XS GIS Cut Line= 2
     2056924.412      158905.866     2056466.513      159721.839
#Sta/Elev= 30
       0 1979.98    39.3 1969.19    78.5 1956.72    98.2 1949.74   114.5 1942.47
   140.7  1932.4   189.8 1916.28   212.6 1906.04   238.8 1896.11   251.9 1890.06
   268.3 1880.66   284.6 1870.18   287.9    1869   294.4 1868.59   300.8 1870.04
   307.5 1871.22  356.04 1871.67   451.5 1871.34     494 1872.02   582.3 1874.82
  673.651880.072   693.6 1881.47  707.52  1883.9   726.3 1884.91  741.391884.551
  750.191885.382   755.7 1886.14  815.351888.745  897.651893.771   935.7 1896.06
#Mann= 10 ,-1 , 0
       0     .12       0   284.6    .045       0   300.8     .12       0
  356.04     .06       0  673.65     .08       0  707.52    .016       0
  741.39     .08       0  750.19     .06       0  815.35     .12       0
  897.65     .06       0
Bank Sta=284.6,300.8
XS Rating Curve= 0 ,0
Exp/Cntr=0.3,0.1

Type RM Length L Ch R = 1 ,47029.8 ,356,357.3,356.6
XS GIS Cut Line= 2
     2056461.088      158618.323     2055918.553      159449.486
#Sta/Elev= 30
       0 1989.05    39.3 1977.04    68.8 1969.39   99.591957.034   137.6 1940.32
     226 1906.66   239.1 1902.47   268.6  1887.9   281.7 1880.44   291.5 1873.16
   298.1 1869.54   307.9 1867.44   327.6 1866.14   350.5  1866.6   357.2 1865.03
   360.3 1864.61   372.2 1865.68  390.051867.348     606 1870.97  682.621877.902
     701 1879.19   720.7 1878.45  727.41 1880.59  742.681881.968   868.1 1888.19
   892.71887.652   920.5 1885.49  934.551891.294   943.4 1893.94   992.6 1896.73
#Mann= 10 ,-1 , 0
       0     .06       0   99.59     .12       0   357.2    .045       0
   372.2     .12       0  390.05     .06       0  682.62    .016       0
  727.41     .08       0  742.68     .06       0   892.7    .016       0
  934.55     .06       0
Bank Sta=357.2,372.2
XS Rating Curve= 0 ,0
Exp/Cntr=0.3,0.1

Type RM Length L Ch R = 1 ,46672.5 ,739.3,740.9,733.6
XS GIS Cut Line= 2
     2056162.694        158489.2     2055608.509       159266.59
#Sta/Elev= 30
       0 1968.25   65.551947.391    85.3 1937.25   131.2 1917.41   200.1 1894.32
   216.5 1885.55   252.6 1863.21   255.9 1862.57   269.7  1864.1  296.451865.637
   383.8 1866.17   436.3 1867.62   498.7 1872.08   547.9 1869.62   593.8 1869.73
   610.2 1870.48  624.95 1872.74   633.2 1874.04   646.3 1874.32   702.1 1873.71
   731.6 1871.69     748 1871.79   777.5 1873.76   787.4 1875.61  837.45 1880.82
  855.131883.551  872.451884.714   915.21887.002  932.371888.068   954.7 1888.87
#Mann= 11 ,-1 , 0
       0     .06       0   65.55     .12       0   252.6    .045       0
   269.7     .12       0  296.45     .06       0  624.95    .016       0
  837.45     .08       0  855.13     .06       0  872.45     .08       0
   915.2     .06       0  932.37     .08       0
Bank Sta=252.6,269.7
XS Rating Curve= 0 ,0
Exp/Cntr=0.3,0.1

Type RM Length L Ch R = 1 ,45931.6 ,429.7,428.3,428.4
XS GIS Cut Line= 3
     2055706.964      157786.075     2055685.263      158057.342
     2055179.895      158861.992
#Sta/Elev= 30
       0  1944.6    65.6 1922.21  120.931906.207  196.84 1889.85   236.1    1883
   298.4 1869.93     318 1870.08   331.1 1868.32   350.8    1870   363.9 1869.17
   373.7 1865.96   383.5 1859.58   390.1 1858.59     403 1860.14  409.981861.069
  436.221861.459   573.6 1860.44   603.1 1862.98   907.8 1864.16   937.3 1865.65
  965.141868.759   976.6 1869.88  991.081873.177  1006.1 1874.36  1025.7    1874
 1037.971876.072  1074.9 1880.77  1137.1 1884.99  1153.5 1887.91  1222.3 1894.84
#Mann= 10 ,-1 , 0
       0     .06       0  120.93     .12       0  196.84     .06       0
   383.5    .045       0     403     .06       0  409.98     .08       0
  436.22     .06       0  965.14     .08       0  991.08    .016       0
 1037.97     .06       0
#XS Ineff= 2 , 0
                          778.75         1883.14
Permanent Ineff=
       F       F
Bank Sta=383.5,403
XS Rating Curve= 0 ,0
Exp/Cntr=0.3,0.1

Type RM Length L Ch R = 1 ,45503.3 ,692.1,703.8,707
XS GIS Cut Line= 3
     2055357.572       157712.29     2055348.892      157835.988
     2054893.603      158747.027
#Sta/Elev= 30
       0 2004.99    16.3 2004.59    35.9 2001.64    97.9 1987.92   173.1 1969.08
  216.37 1954.18   241.9 1942.29   264.8 1927.64   287.7 1914.98   313.9 1895.98
   340.1 1879.25   356.5 1870.68   382.7 1860.08  414.651857.851   420.7 1857.82
   431.8 1856.49   441.7 1858.67   520.3 1857.95   536.6 1859.58     684 1861.18
  836.291871.293   854.3 1873.71   877.2 1873.21  886.941874.275  936.311877.128
   991.8 1879.49  1050.8 1885.34  1080.2 1886.94  1096.6 1891.04  1142.5 1895.27
#Mann= 8 ,-1 , 0
       0     .06       0  216.37     .12       0  414.65     .06       0
   420.7    .045       0   441.7     .06       0  836.29    .016       0
  886.94     .12       0  936.31     .08       0
#XS Ineff= 2 , 0
                          608.48         1894.64
Permanent Ineff=
       F       F
Bank Sta=420.7,441.7
XS Rating Curve= 0 ,0
Exp/Cntr=0.3,0.1

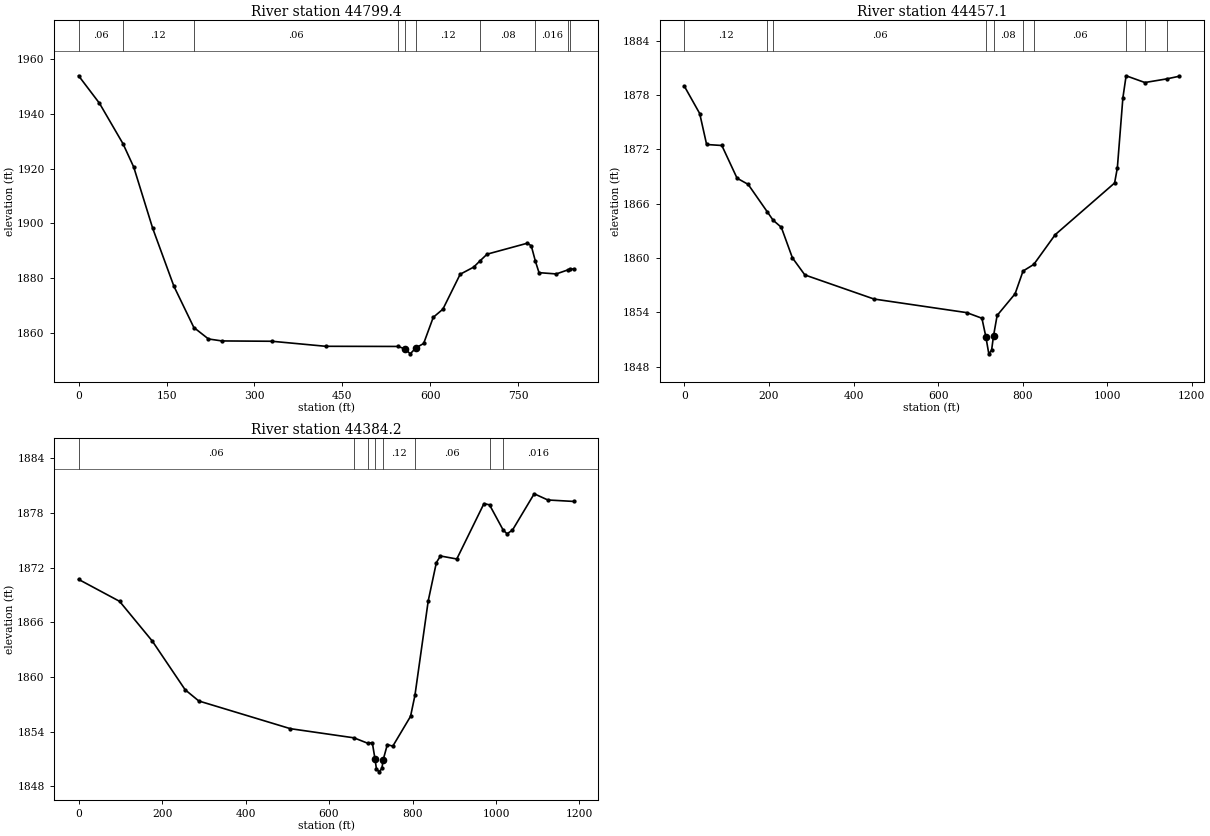
Type RM Length L Ch R = 1 ,44799.4 ,338.3,342.4,345.6
XS GIS Cut Line= 3
     2055127.537      157673.228     2055008.335      157704.128
     2054485.176      158200.571
#Sta/Elev= 30
       0 1953.92    35.6 1943.86   75.681929.086      94 1920.55   126.4 1898.13
   162.5 1876.99  196.581861.862   221.5 1857.67   244.4 1856.95   329.7 1856.83
   421.5 1854.99  544.941854.933   557.4 1853.98   565.7 1852.23   575.5 1854.43
   588.6 1856.02     605 1865.59   621.4 1868.56   650.9 1881.34   673.9 1883.94
  685.061886.299   696.8 1888.68   765.7  1892.7   772.2 1891.73  779.311886.031
   785.4 1881.92   814.8 1881.45  834.811882.945   838.7 1883.12   844.4 1883.33
#Mann= 10 ,-1 , 0
       0     .06       0   75.68     .12       0  196.58     .06       0
  544.94     .12       0   557.4    .045       0   575.5     .12       0
  685.06     .08       0  779.31    .016       0  834.81     .08       0
   838.7     .06       0
Bank Sta=557.4,575.5
XS Rating Curve= 0 ,0
Exp/Cntr=0.3,0.1

Type RM Length L Ch R = 1 ,44457.1 ,72.9,72.9,72.9
XS GIS Cut Line= 3
     2055040.732      157367.238     2054374.499      157825.137
     2054244.291      158163.679
#Sta/Elev= 30
       0 1878.95      36 1875.96    52.4 1872.54    88.4 1872.43   124.4 1868.82
   150.6 1868.14  196.331865.078  209.771864.178   229.1  1863.4   255.3 1860.03
   284.8 1858.14   448.4 1855.48   667.7 1853.98   703.7 1853.36  712.95 1851.33
     720 1849.43   726.6 1849.83   731.1  1851.4   739.7 1853.67   782.2 1856.06
     801 1858.57  826.461859.303     877 1862.58  1017.6 1868.29  1024.1 1869.96
  1037.2 1877.69 1044.821880.126 1089.251879.381 1140.64 1879.78  1171.1 1880.08
#Mann= 10 ,-1 , 0
       0     .12       0  196.33    .016       0  209.77     .06       0
  712.95    .045       0   731.1     .08       0     801    .016       0
  826.46     .06       0 1044.82    .016       0 1089.25     .08       0
 1140.64     .06       0
Bank Sta=712.95,731.1
XS Rating Curve= 0 ,0
Exp/Cntr=0.3,0.1

Type RM Length L Ch R = 1 ,44384.2 ,178.9,169.9,160.3
XS GIS Cut Line= 3
     2054995.159      157310.814     2054328.926      157768.714
     2054166.166      158109.426
#Sta/Elev= 30
       0 1870.72    98.2 1868.31   176.7 1863.94   255.3  1858.6     288 1857.37
   507.3 1854.33  659.851853.323  692.211852.737   703.7 1852.79   710.2 1850.99
   713.5 1849.93     720 1849.59   726.6 1849.96   729.9 1850.94   739.7 1852.58
   752.8 1852.41   795.3 1855.68  805.831857.987   837.7 1868.37   857.2 1872.57
     867 1873.29   906.1 1872.96   971.2 1879.04  984.531878.907 1017.271876.136
  1026.5 1875.73  1039.5 1876.13  1091.6 1880.12  1124.2 1879.44    1186 1879.28
#Mann= 8 ,-1 , 0
       0     .06       0  659.85    .016       0  692.21     .12       0
   710.2    .045       0   729.9     .12       0  805.83     .06       0
  984.53     .08       0 1017.27    .016       0
Bank Sta=710.2,729.9
XS Rating Curve= 0 ,0
Exp/Cntr=0.3,0.1