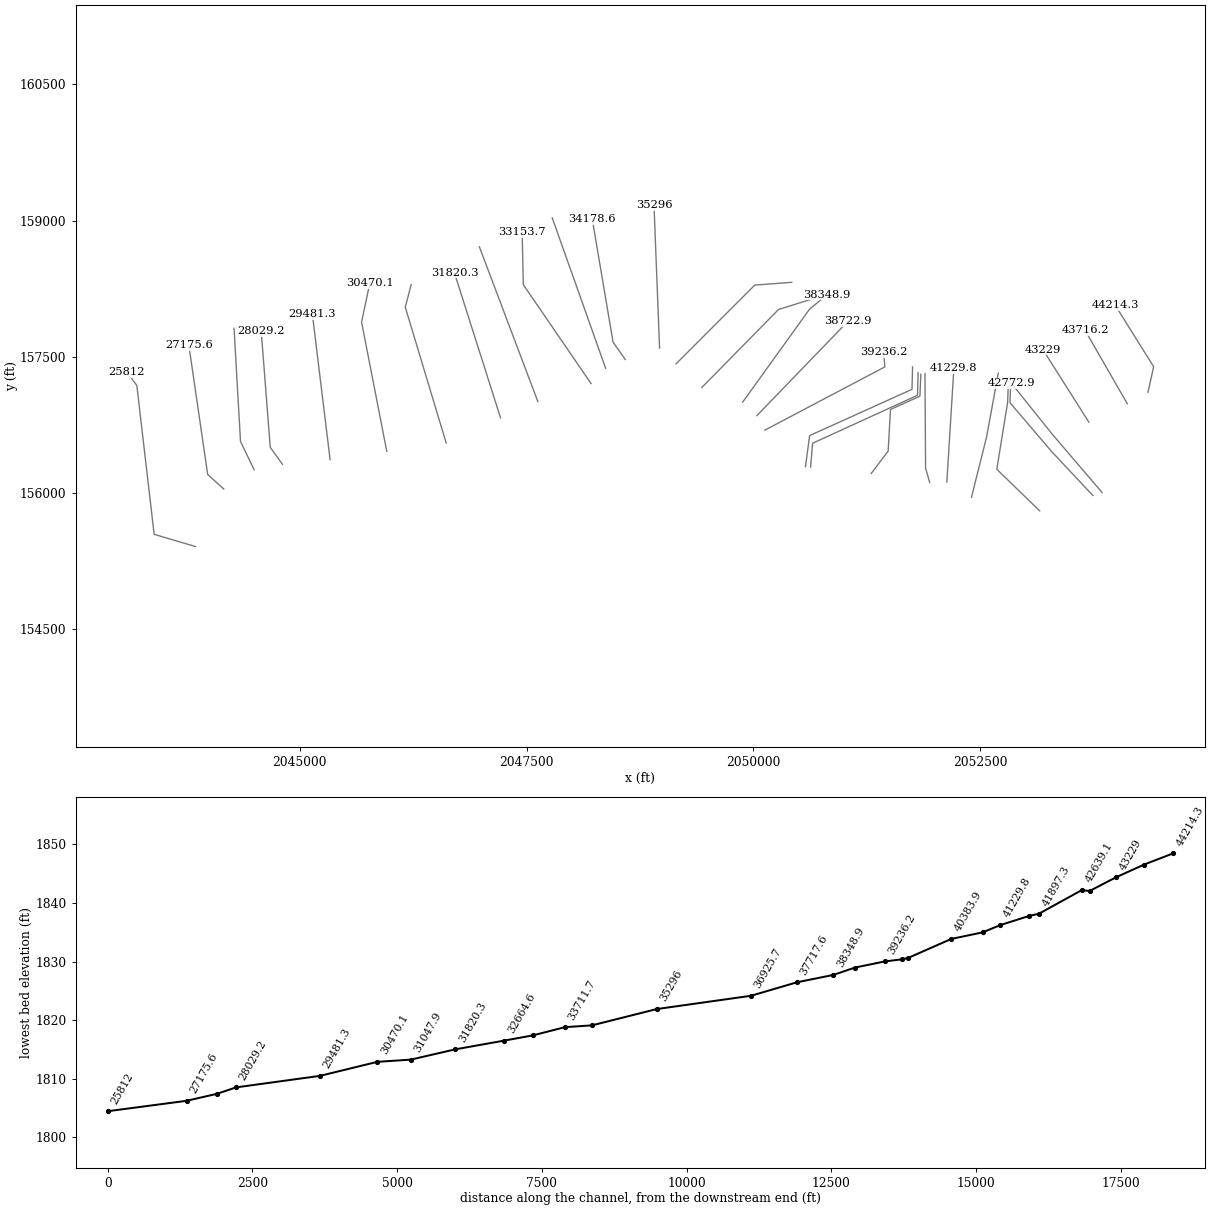
HEC-RAS study RICHCK.prj: RICHCK

--- RICHCK.g01 (geometry) --- (continued)

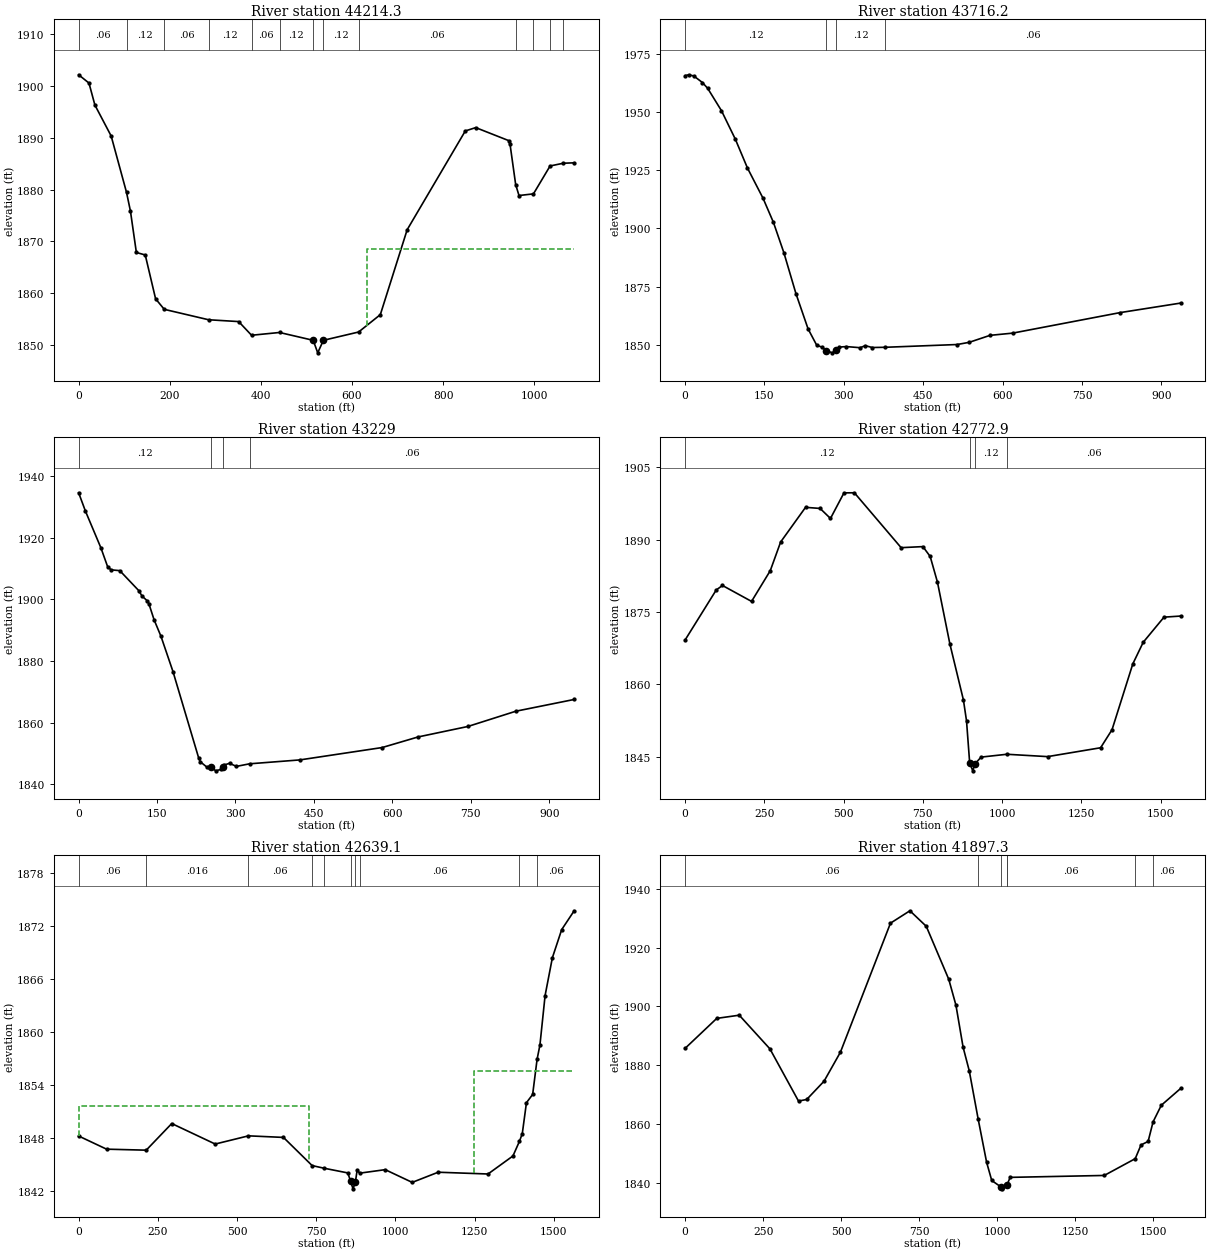
Type RM Length L Ch R = 1 ,44214.3 ,497.6,498.1,496
XS GIS Cut Line= 3
     2054352.798      157106.821     2054415.732      157388.939
     2053992.555      158066.023
#Sta/Elev= 30
       0 1902.19    22.7 1900.59    35.7 1896.34    71.4 1890.36  105.061879.478
   113.7 1875.85   126.7 1867.85   146.2 1867.37   168.9  1858.9  187.941856.864
  285.241854.852   351.2  1854.5  379.481851.857  440.931852.393   514.8 1850.88
   524.7 1848.46   537.1 1850.88  614.381852.482   662.1 1855.84     721 1872.25
   848.6 1891.34   871.5 1891.98   943.5 1889.48   946.8 1888.74  959.121880.974
   966.4 1878.86  998.131879.177 1034.65 1884.57 1063.621885.097  1087.5 1885.18
#Mann= 13 ,-1 , 0
       0     .06       0  105.06     .12       0  187.94     .06       0
  285.24     .12       0  379.48     .06       0  440.93     .12       0
   514.8    .045       0   537.1     .12       0  614.38     .06       0
  959.12    .016       0  998.13     .08       0 1034.65    .016       0
 1063.62     .06       0
#XS Ineff= 2 , 0
                          632.22          1868.5
Permanent Ineff=
       F       F
Bank Sta=514.8,537.1
XS Rating Curve= 0 ,0
Exp/Cntr=0.3,0.1

Type RM Length L Ch R = 1 ,43716.2 ,485.4,487.2,487.4
XS GIS Cut Line= 2
     2054124.933      156980.953     2053658.353      157792.585
#Sta/Elev= 30
       0 1965.59     6.6 1965.98    16.4 1965.47    32.7 1962.65    42.6 1960.18
    68.7 1950.56    94.9 1938.33   117.8 1925.94   147.3 1912.93   166.9 1902.58
   186.6 1889.58   209.5 1871.94   232.4 1856.81   248.8 1849.77   258.6 1849.03
   266.8 1847.51   278.2 1846.56   284.8 1847.73   291.3 1849.03   304.4 1849.25
   330.6 1848.77   340.4 1849.64   353.5 1848.85  377.951848.943   513.9 1850.13
   536.8 1851.08   576.1 1854.07   618.7 1855.02   821.6 1863.83   936.2 1867.93
#Mann= 4 ,-1 , 0
       0     .12       0   266.8    .045       0   284.8     .12       0
  377.95     .06       0
Bank Sta=266.8,284.8
XS Rating Curve= 0 ,0
Exp/Cntr=0.3,0.1

Type RM Length L Ch R = 1 ,43229   ,452.2,456.1,455.3
XS GIS Cut Line= 2
     2053701.756       156776.96     2053194.371      157577.343
#Sta/Elev= 30
       0 1934.52    13.1 1928.54    42.6 1916.67    55.7 1910.44    62.3 1909.53
    78.7 1909.28   114.8 1902.84   121.3 1901.03   131.2 1899.51   134.4 1898.53
   144.3 1893.35   157.4 1888.03   180.4 1876.58   229.5  1848.6   232.8 1847.31
   245.9  1845.5     254 1845.55   262.3 1844.38   272.2 1844.86   275.4 1845.55
   278.7 1846.29   288.6 1846.82   301.7 1845.82  327.111846.664     423 1847.92
   580.4 1851.93   649.3 1855.37   744.4 1858.76   836.2 1863.71   947.7 1867.52
#Mann= 4 ,-1 , 0
       0     .12       0     254    .045       0   275.4     .12       0
  327.11     .06       0
Bank Sta=254,275.4
XS Rating Curve= 0 ,0
Exp/Cntr=0.3,0.1

Type RM Length L Ch R = 1 ,42772.9 ,132.8,133.8,134.1
XS GIS Cut Line= 3
     2053847.155      156002.221      2053298.11      156644.582
     2052848.892      157204.478
#Sta/Elev= 30
       0 1869.19    98.3 1879.58   117.9  1880.5   209.6  1877.2   268.6 1883.57
   301.3 1889.52   379.9 1896.72   425.8 1896.49   458.5 1894.41   501.1 1899.72
   533.9 1899.74   681.3 1888.35     750 1888.57     773 1886.52   795.9  1881.2
   835.2 1868.34   877.8 1856.75   887.6 1852.41   897.5 1843.72   907.3 1842.04
     914 1843.47   933.5 1844.89 1014.941845.479  1143.3 1844.99  1310.5 1846.83
  1346.5 1850.57  1412.1 1864.24  1444.9 1868.72  1510.4 1873.93  1562.9 1874.16
#Mann= 4 ,-1 , 0
       0     .12       0   897.5    .045       0     914     .12       0
 1014.94     .06       0
Bank Sta=897.5,914
XS Rating Curve= 0 ,0
Exp/Cntr=0.3,0.1

Type RM Length L Ch R = 1 ,42639.1 ,760,741.8,711.4
XS GIS Cut Line= 4
     2053745.159      155969.669      2053289.43       156455.78
      2052831.53      156991.804     2052838.041      157184.946
#Sta/Elev= 30
       0 1848.18    88.2 1846.69  213.391846.576     294 1849.59   431.2 1847.27
  536.311848.198   646.7 1848.02  737.221844.833     774 1844.54     850    1844
   858.8 1843.04   866.4  1842.2   873.8 1842.97   879.5 1844.34  887.261843.974
     968 1844.37  1053.2 1842.93  1135.2 1844.08  1292.6 1843.88  1371.3 1845.92
 1391.791847.575  1400.8 1848.45  1413.9 1851.95  1433.5 1852.88 1447.541856.867
  1456.5 1858.48  1472.8 1864.08  1495.8 1868.36  1525.2 1871.54  1564.6 1873.67
#Mann= 10 ,-1 , 0
       0     .06       0  213.39    .016       0  536.31     .06       0
  737.22     .12       0     774     .06       0   858.8    .045       0
   873.8     .08       0  887.26     .06       0 1391.79    .016       0
 1447.54     .06       0
#XS Ineff= 2 , 0
          726.29 1851.62 1247.26          1855.5
Permanent Ineff=
       F       F
Bank Sta=858.8,873.8
XS Rating Curve= 0 ,0
Exp/Cntr=0.3,0.1

Type RM Length L Ch R = 1 ,41897.3 ,175.7,174.2,173.3
XS GIS Cut Line= 4
     2053158.787      155800.398     2052686.131      156258.297
     2052805.489      156996.144     2052811.999      157178.436
#Sta/Elev= 30
       0  1885.8   101.5 1895.97   173.5 1897.05   271.8 1885.63   363.4 1867.93
   389.6 1868.46   445.3 1874.67   497.7  1884.5   658.1 1928.26   720.4 1932.46
   772.8  1927.2   844.9 1909.22   867.9 1900.44   890.8 1886.21   910.5 1878.21
  939.08 1861.83   966.2 1847.16   982.6 1840.99  1011.3 1838.86  1015.4 1838.16
  1031.8 1839.39 1032.851839.839  1041.6 1842.05  1343.2  1842.7 1442.391848.388
  1460.9 1853.04  1483.7 1854.24 1499.571860.875    1526 1866.51  1587.9  1872.2
#Mann= 7 ,-1 , 0
       0     .06       0  939.08     .12       0  1011.3    .045       0
  1031.8     .12       0 1032.85     .06       0 1442.39    .016       0
 1499.57     .06       0
Bank Sta=1011.3,1031.8
XS Rating Curve= 0 ,0
Exp/Cntr=0.3,0.1

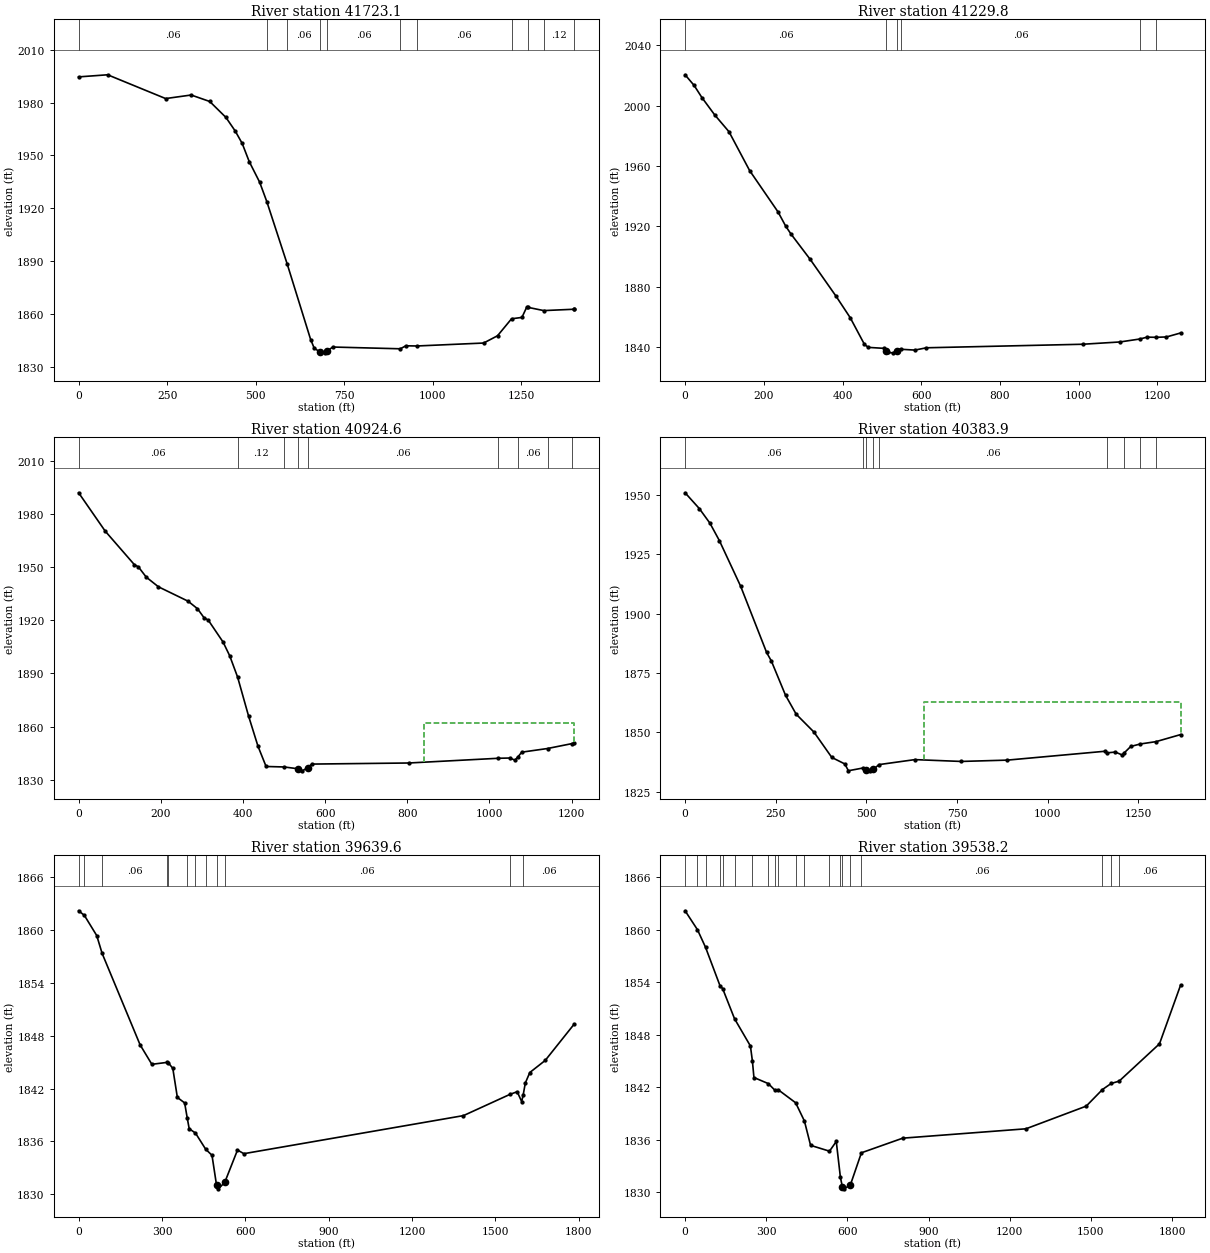
Type RM Length L Ch R = 1 ,41723.1 ,493.1,493.3,490.1
XS GIS Cut Line= 3
     2052407.044      155950.342     2052574.221      156618.025
      2052702.58      157317.931
#Sta/Elev= 30
       0 1994.61    81.9 1995.81   245.8 1982.29   317.9 1984.31   370.4 1980.63
   416.2 1971.55   442.5  1963.8   462.1 1956.77   481.8 1946.52   511.3  1934.8
  531.611923.725  589.451888.103   655.5  1845.3   665.4 1840.48   680.8 1838.34
   694.8 1837.77   701.4 1838.68   717.8 1841.07  908.781840.073   924.4 1841.77
   956.1 1841.67  1144.1 1843.34  1183.4 1847.48 1222.951857.123  1252.3  1857.9
  1265.4 1863.54 1269.861863.606    1314 1861.78 1398.561862.542  1399.9 1862.55
#Mann= 11 ,-1 , 0
       0     .06       0  531.61     .12       0  589.45     .06       0
   680.8    .045       0   701.4     .06       0  908.78     .12       0
   956.1     .06       0 1222.95    .016       0 1269.86     .06       0
    1314     .12       0 1398.56     .06       0
Bank Sta=680.8,701.4
XS Rating Curve= 0 ,0
Exp/Cntr=0.3,0.1

Type RM Length L Ch R = 1 ,41229.8 ,302.2,305.2,305.5
XS GIS Cut Line= 2
     2052134.916      156117.238     2052213.041      157373.748
#Sta/Elev= 30
       0 2020.48      23  2013.4    42.6 2005.42    75.4 1993.82   111.5 1982.75
   163.9 1957.02     236 1929.64   255.7 1920.13   268.8 1915.02     318 1898.08
   383.6  1873.7   419.6 1859.46   455.7 1841.78   465.5 1839.84   504.9  1839.2
   511.4 1837.61   514.7 1836.45   527.8 1836.22   537.7 1837.48     541 1838.42
  549.531838.573   583.6 1838.04   613.1 1839.57  1009.8 1841.91  1104.8 1843.43
 1155.411845.392  1173.7 1846.62 1196.481846.511  1222.9 1846.75  1258.9 1849.39
#Mann= 6 ,-1 , 0
       0     .06       0   511.4    .045       0   537.7     .12       0
  549.53     .06       0 1155.41    .016       0 1196.48     .08       0
Bank Sta=511.4,537.7
XS Rating Curve= 0 ,0
Exp/Cntr=0.3,0.1

Type RM Length L Ch R = 1 ,40924.6 ,492.2,540.7,533
XS GIS Cut Line= 3
     2051946.114      156112.898     2051900.541      156271.318
      2051894.03      157312.985
#Sta/Elev= 30
       0 1992.12    64.6 1970.48   135.8 1951.47   145.4 1950.27   164.8 1944.41
   194.3 1938.98   266.4 1930.86   289.3 1926.62   305.7 1921.38   315.5 1920.19
   351.6 1907.79   367.9 1899.96  387.05 1887.96   413.8 1865.91   436.7 1848.87
   456.4 1837.44   500.41837.169   534.4 1836.14   544.8 1834.98   557.9 1836.86
   567.8  1838.8   803.6 1839.41 1021.561842.078  1049.3 1842.22  1062.4 1841.05
 1070.171843.036  1078.8 1845.53 1141.641847.599 1200.721850.349  1206.5 1850.51
#Mann= 9 ,-1 , 0
       0     .06       0  387.05     .12       0   500.4     .06       0
   534.4    .045       0   557.9     .06       0 1021.56    .016       0
 1070.17     .06       0 1141.64     .08       0 1200.72     .12       0
#XS Ineff= 2 , 0
                          840.47            1862
Permanent Ineff=
       F       F
Bank Sta=534.4,557.9
XS Rating Curve= 0 ,0
Exp/Cntr=0.3,0.1

Type RM Length L Ch R = 1 ,40383.9 ,790.9,744.3,714.6
XS GIS Cut Line= 5
       2051301.8      156212.507     2051488.003       156459.83
     2051513.605      156917.368     2051838.258       157064.07
     2051848.675      157306.257
#Sta/Elev= 30
       0 1950.79    39.1 1944.17    68.4 1938.02    94.5 1930.69   153.2 1911.48
   224.8 1883.63   237.9 1880.04     277 1865.63   306.3 1857.68   355.4 1850.15
   404.5  1839.5   440.5 1836.75   450.3  1833.9  489.71 1835.03   499.4 1834.41
   509.2 1833.86   519.1  1834.5  534.751836.483   633.6 1838.58   761.3 1837.81
   888.8 1838.37  1156.8 1842.08 1162.811841.419  1186.3 1841.75    1206  1840.5
 1210.321841.323  1228.9 1844.11 1255.011845.147 1298.721846.144  1366.5 1849.11
#Mann= 9 ,-1 , 0
       0     .06       0  489.71     .07       0   499.4    .045       0
   519.1     .07       0  534.75     .06       0 1162.81    .016       0
 1210.32     .06       0 1255.01     .08       0 1298.72     .06       0
#XS Ineff= 2 , 0
                          658.24         1862.98
Permanent Ineff=
       F       F
Bank Sta=499.4,519.1
XS Rating Curve= 0 ,0
Exp/Cntr=0.3,0.1

Type RM Length L Ch R = 1 ,39639.6 ,112.2,101.4,93.3
XS GIS Cut Line= 4
     2050632.746      156282.603     2050654.447      156545.189
     2051811.565      157074.269     2051818.076      157321.665
#Sta/Elev= 30
       0 1862.17   20.611861.649    65.1 1859.36   84.521857.336   221.2 1846.96
   263.5 1844.75  317.291844.964  323.071844.914   338.9 1844.29   355.3 1840.99
   381.5 1840.37  390.891838.648   397.9 1837.44  420.511836.948  457.421835.105
   479.9 1834.43   496.3 1831.04   502.9 1830.62   525.8 1831.35   571.7 1835.02
   594.7 1834.61    1385 1838.93 1551.521841.329  1578.2 1841.64  1594.4 1840.52
 1599.821841.272  1607.5 1842.63  1623.7 1843.82  1679.1 1845.19  1783.3 1849.31
#Mann= 12 ,-1 , 0
       0     .06       0   20.61    .016       0   84.52     .06       0
  317.29    .016       0  323.07     .08       0  390.89     .06       0
  420.51     .08       0  457.42     .06       0   496.3    .045       0
   525.8     .06       0 1551.52    .016       0 1599.82     .06       0
Bank Sta=496.3,525.8
XS Rating Curve= 0 ,0
Exp/Cntr=0.3,0.1

Type RM Length L Ch R = 1 ,39538.2 ,300.6,302,303.6
XS GIS Cut Line= 4
     2050576.322      156286.943     2050621.895      156629.825
     2051750.801      157139.373     2051757.312      157386.769
#Sta/Elev= 30
       0 1862.16   45.761859.994   75.561857.987  129.421853.565  138.731853.275
  182.771849.825   241.5 1846.71  248.791845.002   254.5 1843.11  307.631842.413
   331.71841.667  343.761841.721  408.661840.224  441.071838.143   463.9 1835.36
  533.791834.692   558.9  1835.8  574.171831.707   581.8 1830.56   588.4 1830.39
   611.3 1830.86   651.81834.508   804.6 1836.18  1260.1 1837.25  1482.9 1839.84
 1542.961841.738 1575.361842.431 1604.581842.694  1753.8 1846.96    1832 1853.68
#Mann= 20 ,-1 , 0
       0     .06       0   45.76     .12       0   75.56    .016       0
  129.42     .06       0  138.73     .08       0  182.77     .06       0
  248.79    .016       0  307.63     .12       0   331.7     .08       0
  343.76     .12       0  408.66    .016       0  441.07     .06       0
  533.79     .12       0  574.17     .06       0   581.8    .045       0
   611.3     .12       0   651.8     .06       0 1542.96     .08       0
 1575.36     .12       0 1604.58     .06       0
Bank Sta=581.8,611.3
XS Rating Curve= 0 ,0
Exp/Cntr=0.3,0.1

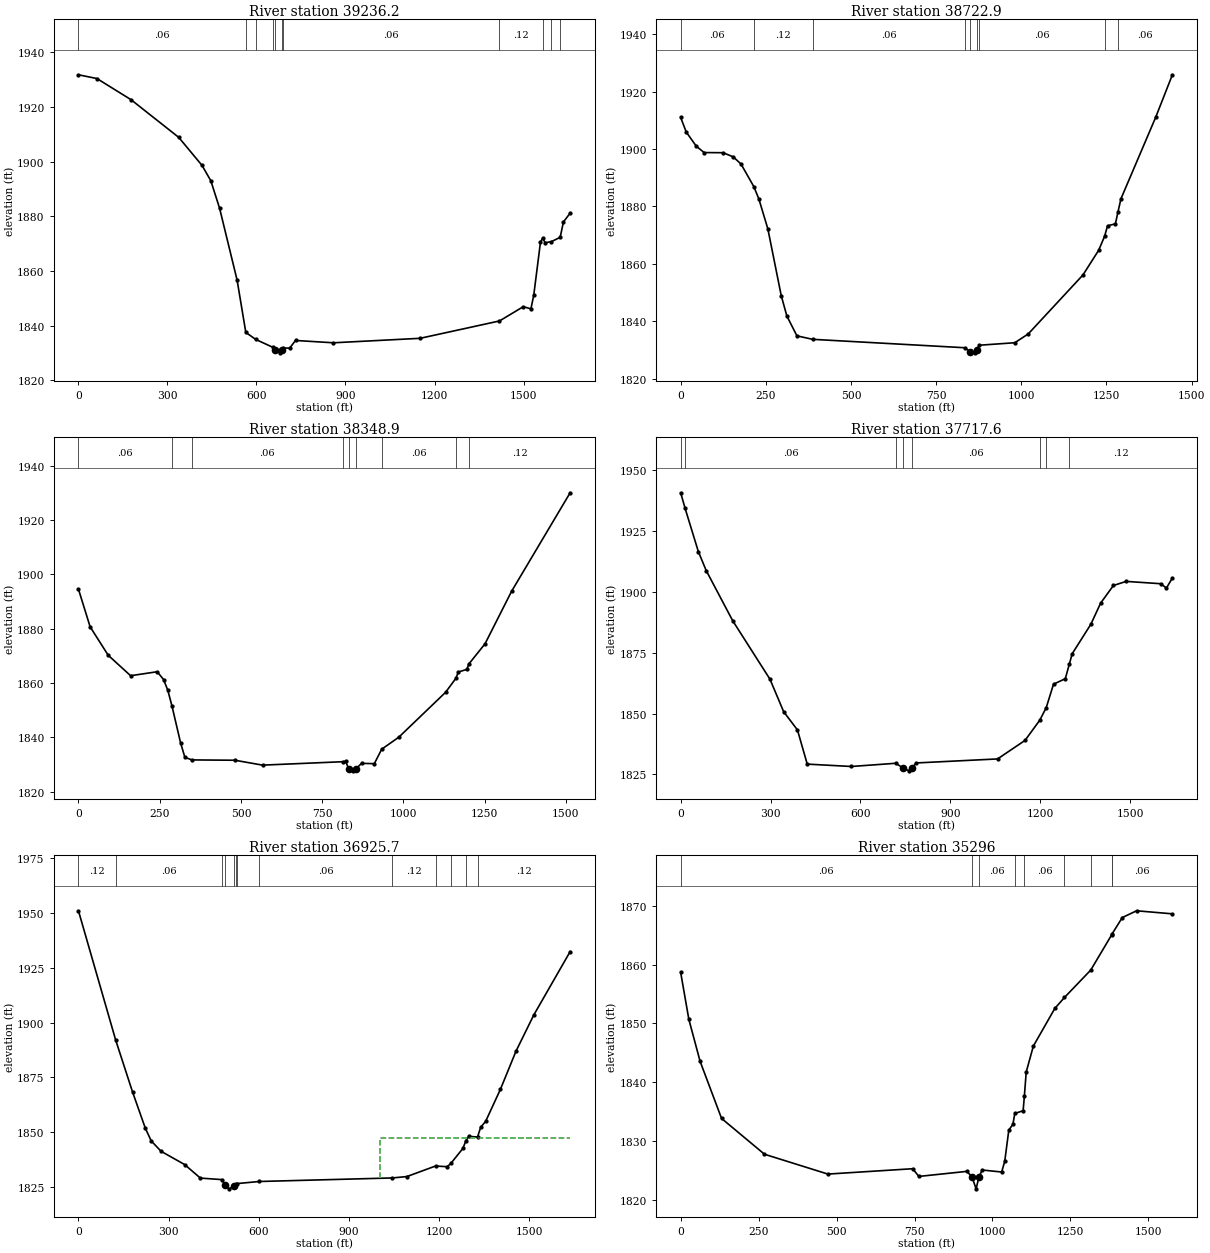
Type RM Length L Ch R = 1 ,39236.2 ,504.5,513.2,518.7
XS GIS Cut Line= 3
     2050127.755      156689.597     2051451.322      157386.769
     2051438.301       157547.36
#Sta/Elev= 30
       0 1931.84    62.3 1930.46   177.2 1922.72   337.9 1908.93   416.6 1898.64
   446.2 1893.02   475.7 1882.96   534.7 1856.66  564.091837.491  597.691834.924
  656.531831.976   660.9 1830.92   679.1 1830.02   685.6 1830.88  689.911831.785
   711.9 1831.76   731.6 1834.55   859.5  1833.7  1151.5 1835.34 1418.88 1841.69
  1499.2 1846.92    1525 1846.13  1534.6 1851.24  1557.2 1870.62 1564.26 1871.94
  1573.3 1870.36  1593.9 1870.74 1623.54 1872.32  1634.5 1877.96  1657.1 1881.17
#Mann= 11 ,-1 , 0
       0     .06       0  564.09    .016       0  597.69     .06       0
  656.53     .08       0   660.9    .045       0   685.6     .08       0
  689.91     .06       0 1418.88     .12       0 1564.26     .08       0
  1593.9    .016       0 1623.54     .06       0
Bank Sta=660.9,685.6
XS Rating Curve= 0 ,0
Exp/Cntr=0.3,0.1

Type RM Length L Ch R = 1 ,38722.9 ,368.1,374.1,376.3
XS GIS Cut Line= 2
     2050040.388      156850.084     2051043.336      157888.071
#Sta/Elev= 30
       0    1911    16.4 1905.91    45.9 1900.98    68.9 1898.77   124.6 1898.72
   154.2 1897.28   177.1 1894.78  214.931886.858   229.6 1882.57   255.9 1872.18
   295.2 1848.91   311.6 1841.84   341.2  1834.9  387.571833.687  834.111830.757
   849.6 1829.37   862.7 1828.98   868.7 1830.05  876.621831.632   980.8  1832.5
  1020.2 1835.56  1180.9 1856.12  1226.9  1864.7  1244.41869.583  1253.1 1873.26
  1276.1 1873.92 1283.541878.009  1292.5 1882.69  1394.2 1911.01  1443.4 1925.88
#Mann= 9 ,-1 , 0
       0     .06       0  214.93     .12       0  387.57     .06       0
  834.11     .08       0   849.6    .045       0   868.7     .08       0
  876.62     .06       0  1244.4    .016       0 1283.54     .06       0
Bank Sta=849.6,868.7
XS Rating Curve= 0 ,0
Exp/Cntr=0.3,0.1

Type RM Length L Ch R = 1 ,38348.9 ,630.9,631.2,625.3
XS GIS Cut Line= 3
     2049884.048      156998.748     2050622.329       158024.79
     2050814.603      158182.776
#Sta/Elev= 30
       0 1894.61      36 1880.73    91.7 1870.25   160.5 1862.74   242.3  1864.2
     262 1861.32   275.1 1857.34  287.861851.537   314.4 1837.96   327.5  1832.7
   348.91831.743   481.4 1831.62   566.5 1829.82  813.43 1831.08     822 1831.21
   831.8 1828.42   844.9 1827.72   853.8 1828.47   871.1 1830.47   910.4 1830.36
  933.091835.687   985.7  1840.1  1129.8 1856.65 1161.341861.776  1169.1 1864.12
  1195.3 1865.07 1200.991867.017    1251 1874.48  1332.8 1893.83  1512.9 1930.08
#Mann= 9 ,-1 , 0
       0     .06       0  287.86     .12       0   348.9     .06       0
  813.43     .12       0   831.8    .045       0   853.8     .12       0
  933.09     .06       0 1161.34    .016       0 1200.99     .12       0
Bank Sta=831.8,853.8
XS Rating Curve= 0 ,0
Exp/Cntr=0.3,0.1

Type RM Length L Ch R = 1 ,37717.6 ,793,792,781.8
XS GIS Cut Line= 3
     2049432.659      157159.339     2050279.881       158020.45
     2050693.076      158148.922
#Sta/Elev= 30
       0 1940.67   14.741934.269    58.9 1916.54    85.1 1908.73   173.5 1888.13
   297.9  1864.1   343.7 1850.73   389.6 1843.27   422.3 1829.22   569.6 1828.25
   717.91829.568   743.1 1827.51   762.8 1826.46   772.6  1827.7   785.7  1829.7
  1057.4 1831.35  1149.1 1838.97 1198.09 1847.24 1219.69 1852.39  1244.1 1862.05
  1283.4 1864.31 1296.811870.271  1306.4 1874.56  1368.6 1886.65  1401.4 1895.37
    1444 1902.59  1486.6 1904.27  1601.4 1903.32    1621 1901.55  1640.7 1905.68
#Mann= 8 ,-1 , 0
       0     .12       0   14.74     .06       0   717.9     .12       0
   743.1    .045       0   772.6     .06       0 1198.09     .12       0
 1219.69    .016       0 1296.81     .12       0
Bank Sta=743.1,772.6
XS Rating Curve= 0 ,0
Exp/Cntr=0.3,0.1

Type RM Length L Ch R = 1 ,36925.7 ,1604.9,1629.7,1550
XS GIS Cut Line= 3
     2049148.805      157420.623      2050016.86      158288.679
     2050424.846      158319.061
#Sta/Elev= 30
       0 1951.01  124.051891.985     180 1868.39   222.6 1851.83   242.2 1846.04
     275 1841.29   353.6 1835.23   405.9 1829.06  478.531828.363   487.8 1825.69
   500.9 1824.16   517.2 1825.23  524.361826.401  527.031826.546  601.961827.509
  1045.1 1829.13  1093.4 1829.77 1188.541834.568  1227.6 1834.26 1239.941835.814
    1280 1842.63 1289.421846.089  1299.6  1848.1  1328.51847.785  1338.9 1852.27
  1355.3 1854.91  1404.4  1869.5  1456.7 1887.02  1515.6 1903.45  1636.7 1932.38
#Mann= 13 ,-1 , 0
       0     .12       0  124.05     .06       0  478.53     .12       0
   487.8    .045       0   517.2     .12       0  524.36     .06       0
  527.03     .12       0  601.96     .06       0  1045.1     .12       0
 1188.54     .06       0 1239.94     .12       0 1289.42    .016       0
  1328.5     .12       0
#XS Ineff= 2 , 0
                         1005.31         1847.33
Permanent Ineff=
       F       F
Bank Sta=487.8,517.2
XS Rating Curve= 0 ,0
Exp/Cntr=0.3,0.1

Type RM Length L Ch R = 1 ,35296   ,1110.4,1117.4,1114.6
XS GIS Cut Line= 2
     2048967.291      157593.942     2048905.749      159169.755
#Sta/Elev= 30
       0 1858.67    26.2  1850.7    62.3 1843.56   131.1 1833.86   268.8 1827.77
   472.1  1824.4   744.2 1825.31   763.9    1824     918 1824.86   934.4 1823.91
   947.5 1821.89   956.7 1823.92   967.2 1825.09  1029.5 1824.75  1039.3 1826.56
  1052.4 1831.88  1065.6 1832.86 1071.541834.701  1098.3 1835.17 1102.27 1837.62
  1108.2 1841.75  1131.1 1846.16    1200 1852.56 1230.881854.421 1315.181859.081
 1382.491865.085 1383.741865.237  1416.4 1868.01  1462.3 1869.16    1577 1868.64
#Mann= 9 ,-1 , 0
       0     .06       0   934.4    .045       0   956.7     .06       0
 1071.54    .016       0 1102.27     .06       0 1230.88     .08       0
 1315.18     .06       0 1382.49     .08       0 1383.74     .06       0
Bank Sta=934.4,956.7
XS Rating Curve= 0 ,0
Exp/Cntr=0.3,0.1

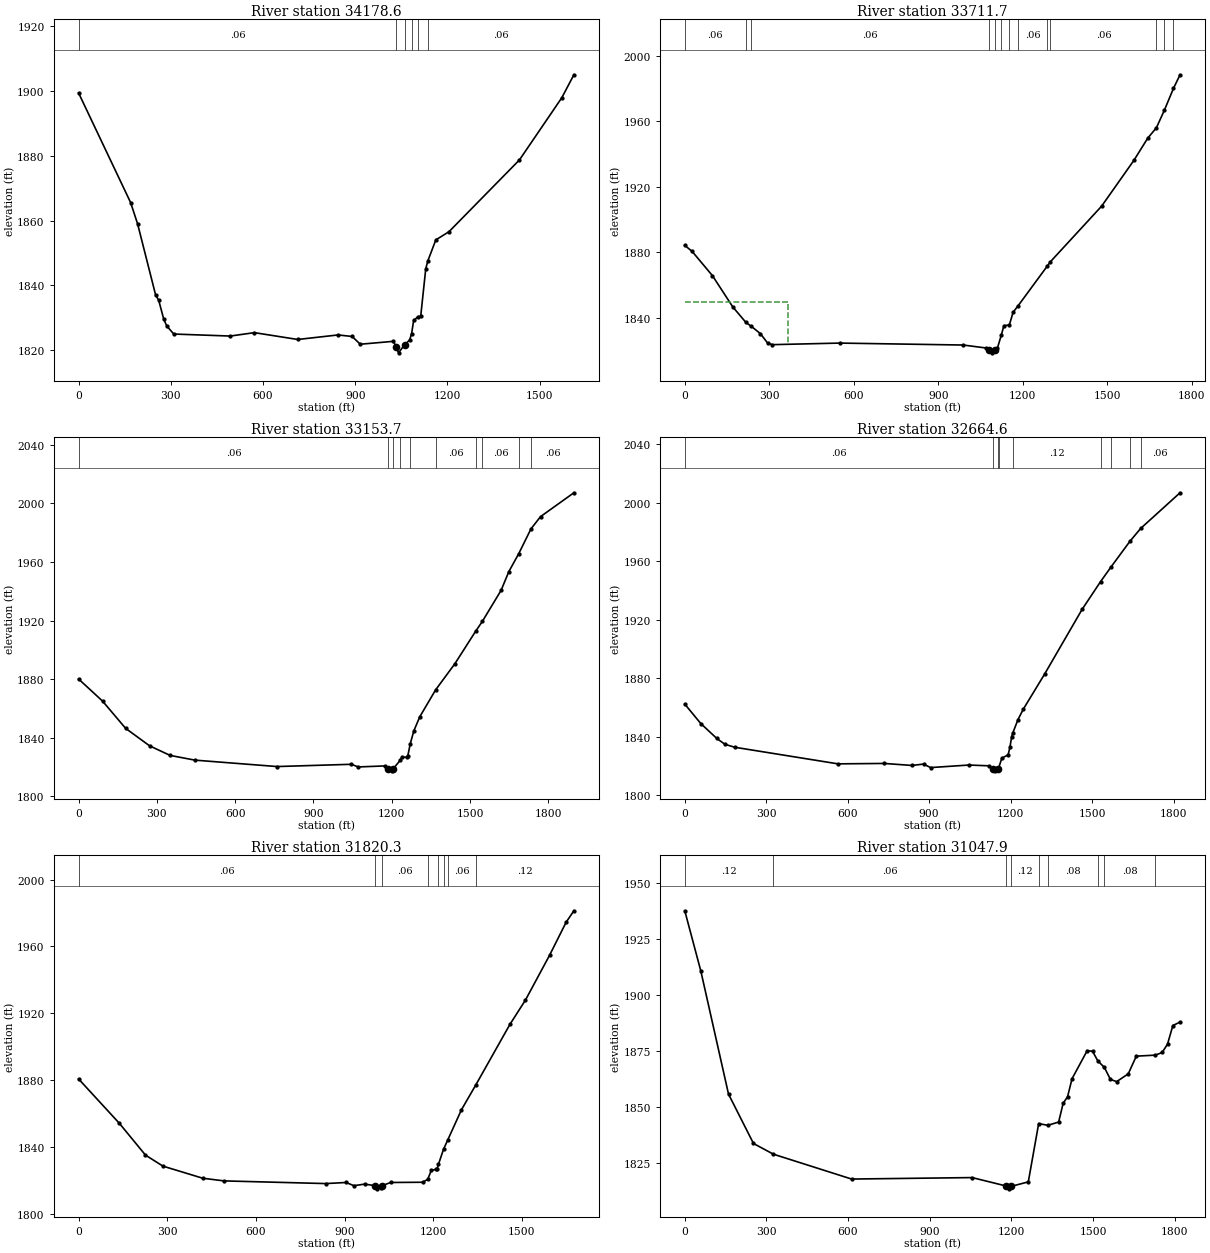
Type RM Length L Ch R = 1 ,34178.6 ,462.4,466.9,452.7
XS GIS Cut Line= 3
     2048588.909      157468.366     2048454.331      157660.069
     2048224.326      159017.846
#Sta/Elev= 30
       0 1899.42   169.2 1865.56   191.9 1858.97   250.6 1836.97   260.5  1835.4
   276.8 1829.56   286.7 1827.42   309.6 1824.92   493.2  1824.3     572 1825.35
   712.9 1823.24   844.1 1824.64     890 1824.17   916.2 1821.77  1024.4 1822.67
  1033.2  1820.9  1040.8 1819.11  1060.5 1821.59  1076.9 1823.08 1083.43 1825.07
    1090 1829.12 1104.491830.296    1113 1830.44  1129.4  1845.1 1135.981847.473
  1162.1 1854.02  1204.8 1856.54  1434.3 1878.75    1572 1897.96  1611.3 1905.06
#Mann= 6 ,-1 , 0
       0     .06       0  1033.2    .045       0  1060.5     .12       0
 1083.43    .016       0 1104.49     .08       0 1135.98     .06       0
Bank Sta=1033.2,1060.5
XS Rating Curve= 0 ,0
Exp/Cntr=0.3,0.1

Type RM Length L Ch R = 1 ,33711.7 ,550.4,558,562.6
XS GIS Cut Line= 2
     2048371.895       157372.88     2047783.333      159030.324
#Sta/Elev= 30
       0 1884.35    26.2 1880.64    98.3 1865.86   170.3 1846.85  217.171837.334
  236.561834.945   268.6 1830.49   294.8 1824.64   311.2 1823.79   550.2 1824.75
   989.1 1823.56    1071 1821.73  1080.8 1820.29  1090.7  1818.8  1100.5 1820.34
  1110.3 1821.69 1123.841829.449  1133.3 1835.36 1152.58 1835.76    1166 1843.54
 1183.931847.543 1287.491871.736 1298.621874.378  1480.4 1908.26  1595.1 1936.22
  1644.2 1949.74 1674.891956.058 1703.271966.781 1735.411980.046  1758.8 1988.37
#Mann= 13 ,-1 , 0
       0     .06       0  217.17     .08       0  236.56     .06       0
  1080.8    .045       0  1100.5     .08       0 1123.84    .016       0
 1152.58     .08       0 1183.93     .06       0 1287.49     .08       0
 1298.62     .06       0 1674.89     .08       0 1703.27     .06       0
 1735.41     .08       0
#XS Ineff= 2 , 0
          366.31 1849.76
Permanent Ineff=
       F       F
Bank Sta=1080.8,1100.5
XS Rating Curve= 0 ,0
Exp/Cntr=0.3,0.1

Type RM Length L Ch R = 1 ,33153.7 ,491,489,481.2
XS GIS Cut Line= 3
     2048211.305       157203.61     2047464.777      158293.019
     2047451.756      158870.276
#Sta/Elev= 30
       0 1880.09    91.8 1865.01   180.2  1846.4     272 1834.47   350.6 1827.93
   445.7  1824.7   760.3 1820.32  1045.4 1821.86  1071.6 1820.05  1173.2 1820.75
  1186.3 1818.55  1199.4 1817.39    1206 1818.92 1233.091824.703  1238.7 1826.66
  1258.4 1826.73  1261.7 1827.82 1271.181836.004  1284.6 1844.66  1307.5 1854.34
 1368.221872.717    1442 1890.56 1521.22 1912.64  1547.31919.485  1619.2 1940.71
  1648.7 1953.45 1686.911965.792  1733.41982.598  1770.1    1991    1898 2007.31
#Mann= 10 ,-1 , 0
       0     .06       0  1186.3    .045       0    1206     .06       0
 1233.09    .016       0 1271.18     .08       0 1368.22     .06       0
 1521.22     .08       0  1547.3     .06       0 1686.91     .08       0
  1733.4     .06       0
Bank Sta=1186.3,1206
XS Rating Curve= 0 ,0
Exp/Cntr=0.3,0.1

Type RM Length L Ch R = 1 ,32664.6 ,842.5,844.4,839.6
XS GIS Cut Line= 2
     2047625.367      157003.957     2046980.187      158709.979
#Sta/Elev= 30
       0  1862.2      59 1848.88   118.1 1838.65   147.6 1834.71   183.7 1832.66
   564.2 1821.29   734.8 1821.57   836.5  1820.2   879.2 1821.12   905.4 1818.74
  1046.5 1820.48  1121.9 1819.94  1133.8 1817.89  1141.6 1816.51  1154.7 1817.96
 1155.991818.558  1167.8 1825.25  1190.8 1827.42  1197.4 1832.62  1203.9 1839.91
  1208.21842.489  1226.9  1851.5  1246.6 1858.69  1325.3 1882.77  1463.1 1926.97
 1531.081945.981 1570.531956.254 1638.861973.492 1678.851982.419  1823.9 2006.83
#Mann= 9 ,-1 , 0
       0     .06       0  1133.8    .045       0  1154.7     .06       0
 1155.99    .016       0  1208.2     .12       0 1531.08     .06       0
 1570.53     .12       0 1638.86     .08       0 1678.85     .06       0
Bank Sta=1133.8,1154.7
XS Rating Curve= 0 ,0
Exp/Cntr=0.3,0.1

Type RM Length L Ch R = 1 ,31820.3 ,772.2,772.4,770
XS GIS Cut Line= 2
     2047213.041      156826.005     2046705.228      158423.228
#Sta/Elev= 30
       0 1880.73   137.8 1854.23   226.3 1835.19   285.4  1828.6   419.8 1821.38
     492 1819.77   836.4 1818.17   905.2 1818.82   931.5 1816.91   967.6 1817.83
  1003.6 1816.95  1010.2 1815.02  1023.3 1815.69  1026.6 1816.92  1056.1 1818.82
  1164.4 1818.96 1181.44 1820.73  1193.9  1826.2  1210.3 1826.61  1213.6 1827.14
 1217.551829.585  1234.81838.652 1248.551844.009  1295.5 1862.31 1344.121877.174
  1459.5 1913.38    1512  1927.9    1594 1954.83  1649.8 1974.51    1676 1981.36
#Mann= 8 ,-1 , 0
       0     .06       0  1003.6    .045       0  1026.6     .06       0
 1181.44    .016       0 1217.55     .08       0  1234.8     .12       0
 1248.55     .06       0 1344.12     .12       0
Bank Sta=1003.6,1026.6
XS Rating Curve= 0 ,0
Exp/Cntr=0.3,0.1

Type RM Length L Ch R = 1 ,31047.9 ,578.8,577.8,574.6
XS GIS Cut Line= 3
     2046614.082      156548.228     2046162.694      158045.623
     2046227.798      158293.019
#Sta/Elev= 30
       0 1937.74      59 1910.77   160.7 1855.67   252.5 1833.56  325.931828.759
   613.1 1817.64  1055.8  1818.3  1180.3 1814.55  1190.2 1813.26    1200 1814.39
  1262.3 1816.38 1300.411842.486 1333.741841.684  1373.8 1843.17  1390.2 1851.52
  1406.6 1854.51    1423 1862.57  1478.7 1875.12  1498.4 1874.84 1517.751870.529
 1541.781867.619    1564 1862.26  1586.9 1861.25  1629.6 1864.74  1659.1 1872.66
 1729.451873.119  1754.2 1874.31  1773.8 1878.04  1793.5 1886.38  1819.8  1887.9
#Mann= 9 ,-1 , 0
       0     .12       0  325.93     .06       0  1180.3    .045       0
    1200     .12       0 1300.41    .016       0 1333.74     .08       0
 1517.75     .06       0 1541.78     .08       0 1729.45     .06       0
Bank Sta=1180.3,1200
XS Rating Curve= 0 ,0
Exp/Cntr=0.3,0.1

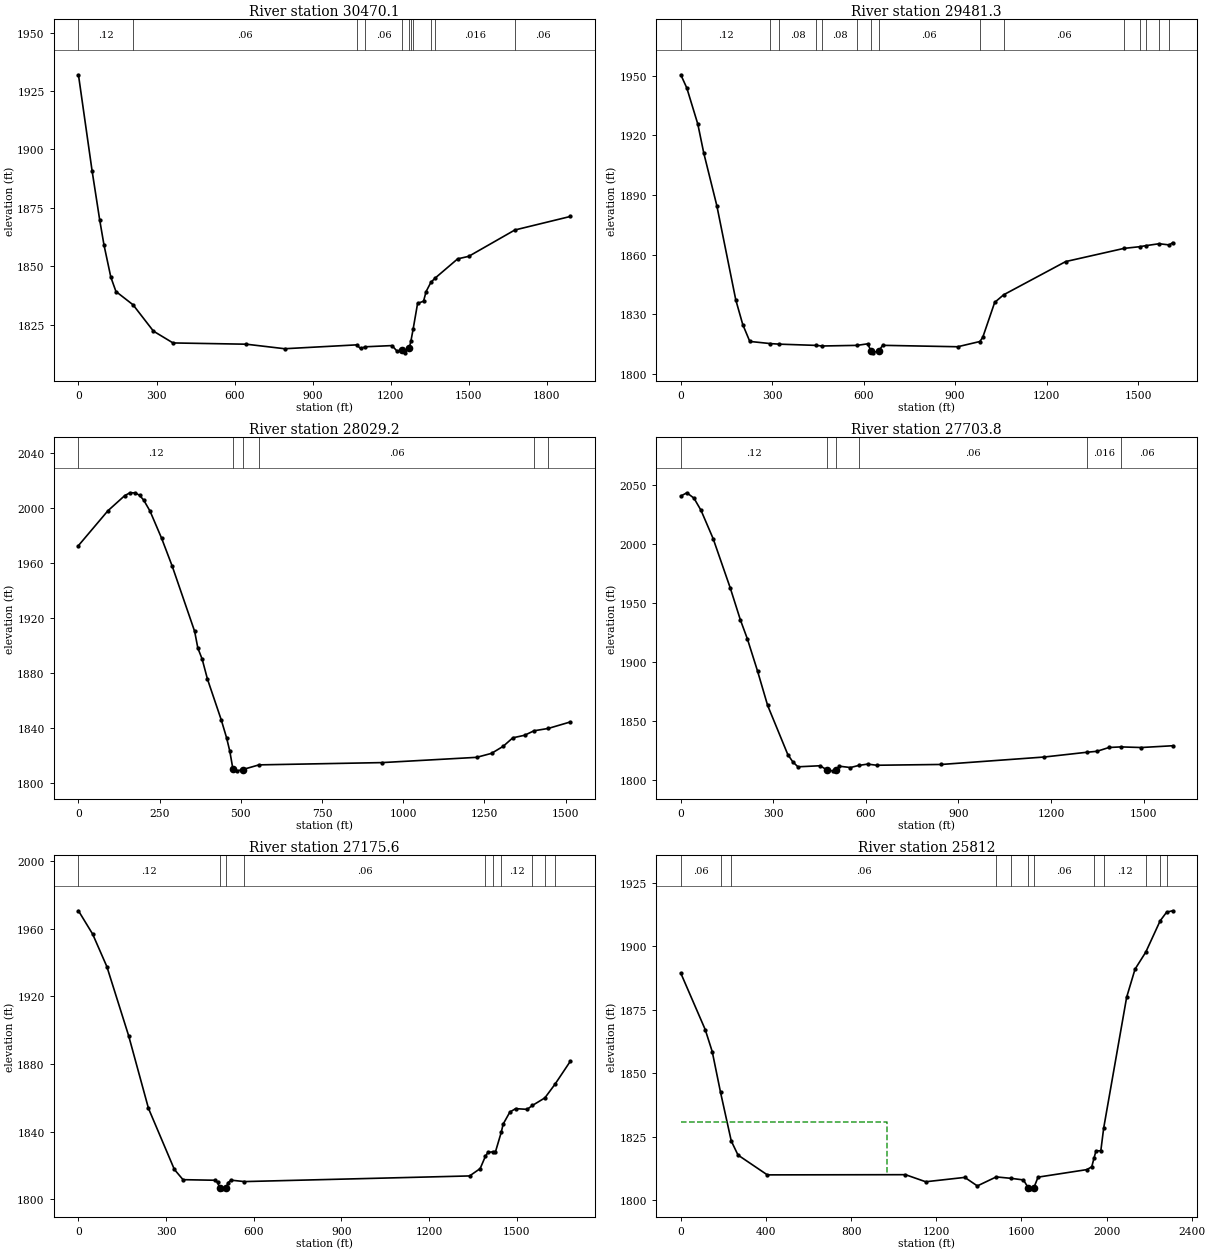
Type RM Length L Ch R = 1 ,30470.1 ,988,988.8,982.5
XS GIS Cut Line= 3
     2045958.701      156457.082     2045680.923      157880.693
     2045772.069       158310.38
#Sta/Elev= 30
       0 1931.99    52.4 1890.87    81.8 1869.71    98.2 1859.05   124.4 1845.31
   144.1 1839.15  209.82 1833.46   288.1 1822.18   363.4 1817.12     645 1816.58
   792.4 1814.64 1068.591816.295  1083.8 1814.74 1102.691815.477  1204.9 1815.99
  1224.5 1813.56  1244.2 1814.17    1254 1812.88  1270.4  1814.8 1277.161817.739
    12861823.056  1303.1 1834.05    1326 1835.01  1335.9 1839.15 1354.141843.067
  1369.51844.801    1457 1853.13  1499.6 1854.22 1676.771865.501  1889.7 1871.29
#Mann= 11 ,-1 , 0
       0     .12       0  209.82     .06       0 1068.59     .12       0
 1102.69     .06       0  1244.2    .045       0  1270.4     .06       0
 1277.16     .12       0    1286    .016       0 1354.14     .06       0
  1369.5    .016       0 1676.77     .06       0
Bank Sta=1244.2,1270.4
XS Rating Curve= 0 ,0
Exp/Cntr=0.3,0.1

Type RM Length L Ch R = 1 ,29481.3 ,1082.7,1452.1,1451.3
XS GIS Cut Line= 2
     2045333.701      156365.936     2045138.388      157967.498
#Sta/Elev= 30
       0 1950.52    19.7 1943.86    55.8 1925.67    75.4 1911.04   118.1 1884.64
   180.4  1837.1   203.3  1824.7   226.3 1816.24   293.21815.154  322.961814.865
  442.951814.242  464.551813.937  577.981814.253   613.2 1815.03   623.1 1811.66
   629.5 1810.49   649.3 1811.56   662.4 1814.27   908.4 1813.56     9811816.191
   990.4 1818.24  1029.7  1835.9 1059.051839.724  1262.5 1856.45 1453.771863.089
    15061863.954 1525.32 1864.46 1569.121865.438 1602.56 1864.83  1613.4 1865.97
#Mann= 15 ,-1 , 0
       0     .12       0   293.2     .06       0  322.96     .08       0
  442.95     .06       0  464.55     .08       0  577.98     .06       0
   623.1    .045       0   649.3     .06       0     981     .12       0
 1059.05     .06       0 1453.77     .12       0    1506     .08       0
 1525.32     .12       0 1569.12    .016       0 1602.56     .08       0
Bank Sta=623.1,649.3
XS Rating Curve= 0 ,0
Exp/Cntr=0.3,0.1

Type RM Length L Ch R = 1 ,28029.2 ,326.5,325.4,324.2
XS GIS Cut Line= 3
     2044808.527      156313.853     2044673.978      156500.485
     2044574.152      157780.866
#Sta/Elev= 30
       0 1972.39    90.7 1997.73   142.6 2008.76   158.8 2010.81     175 2010.75
     188 2008.98   200.9  2005.5   220.4 1997.48   256.3 1977.59     289 1957.24
   357.8 1909.97   367.7 1897.76   380.8 1889.89   397.2 1875.29   439.8 1845.52
   456.1 1832.57     466 1822.86   475.8 1809.57   488.9 1808.52   505.3 1809.43
  555.931812.859   934.5 1814.51    1226 1818.34  1271.9 1821.24  1307.9 1826.39
  1337.4 1832.54  1373.5 1834.39 1402.691837.663 1446.431839.356  1514.3 1844.07
#Mann= 6 ,-1 , 0
       0     .12       0   475.8    .045       0   505.3     .12       0
  555.93     .06       0 1402.69    .016       0 1446.43     .06       0
Bank Sta=475.8,505.3
XS Rating Curve= 0 ,0
Exp/Cntr=0.3,0.1

Type RM Length L Ch R = 1 ,27703.8 ,524.8,528.1,529.4
XS GIS Cut Line= 3
     2044496.027      156253.089     2044345.802      156565.859
     2044274.673      157811.248
#Sta/Elev= 30
       0 2040.42    19.6  2043.2    42.6 2038.65    65.5 2028.31   104.8 2004.33
   160.4 1962.41   193.1 1935.43     216 1919.16   248.8 1891.99   281.5 1862.86
     347 1821.14   363.4 1814.94   379.7 1810.85   451.8 1811.75   474.7 1807.99
   494.3 1807.43   504.1 1807.99     514 1811.36     550 1810.23  577.27 1812.03
   605.6 1813.13   635.1 1812.17   844.6 1812.84  1178.6 1819.16 1318.021823.231
  1348.8 1823.98  1388.1 1827.23 1426.571827.722  1492.9 1827.21  1594.4  1828.7
#Mann= 6 ,-1 , 0
       0     .12       0   474.7    .045       0   504.1     .12       0
  577.27     .06       0 1318.02    .016       0 1426.57     .06       0
Bank Sta=474.7,504.1
XS Rating Curve= 0 ,0
Exp/Cntr=0.3,0.1

Type RM Length L Ch R = 1 ,27175.6 ,1359.5,1363.6,1355.8
XS GIS Cut Line= 3
     2044161.826      156040.415     2043983.874      156201.005
     2043775.541      157628.957
#Sta/Elev= 30
       0  1970.6    48.6 1956.82    97.2 1937.62   171.7 1896.76   239.7 1853.75
   328.2  1817.7   357.8 1811.65     466 1811.31   475.8 1810.11   483.1 1806.85
   492.2 1806.23   505.4 1806.81   511.9 1809.81   521.8 1811.37  567.741810.518
  1338.4 1813.86  1374.5  1818.2 1392.241825.363  1400.7 1827.72 1416.881828.113
    1427 1828.18 1446.731839.694  1453.2 1844.51  1476.2 1851.62  1495.8 1853.64
  1535.2 1853.22 1553.471855.538 1595.991860.003 1630.281867.995  1682.8 1881.59
#Mann= 10 ,-1 , 0
       0     .12       0   483.1    .045       0   505.4     .12       0
  567.74     .06       0 1392.24    .016       0 1416.88     .08       0
 1446.73     .12       0 1553.47    .016       0 1595.99     .06       0
 1630.28     .12       0
Bank Sta=483.1,505.4
XS Rating Curve= 0 ,0
Exp/Cntr=0.3,0.1

Type RM Length L Ch R = 1 ,25812   ,834.4,850.1,862.2
XS GIS Cut Line= 4
     2043849.326      155406.735     2043393.596      155541.283
     2043202.624      157181.908     2043094.117      157329.478
#Sta/Elev= 30
       0 1889.44   114.7  1867.2   147.5 1858.56  186.651842.458     2371823.301
   268.7 1817.76   406.4 1809.95  1055.2 1810.03  1150.3 1807.24  1333.8 1808.96
  1392.8  1805.6 1481.511809.149 1551.621808.587  1609.1 1807.96    1632 1804.88
  1638.6 1804.45  1658.2 1804.87  1677.9 1809.06  1907.3 1812.03  1930.2 1813.15
 1941.331816.742  1949.9 1819.36  1972.8 1819.49 1986.121828.365  2094.1 1879.98
  2133.4 1891.02 2184.051897.777 2251.341910.068 2281.831913.503    2310 1914.04
#Mann= 12 ,-1 , 0
       0     .06       0  186.65     .12       0     237     .06       0
 1481.51     .12       0 1551.62     .06       0    1632    .045       0
  1658.2     .06       0 1941.33    .016       0 1986.12     .12       0
 2184.05     .06       0 2251.34     .08       0 2281.83    .016       0
#XS Ineff= 2 , 0
          969.47 1830.71
Permanent Ineff=
       F       F
Bank Sta=1632,1658.2
XS Rating Curve= 0 ,0
Exp/Cntr=0.3,0.1