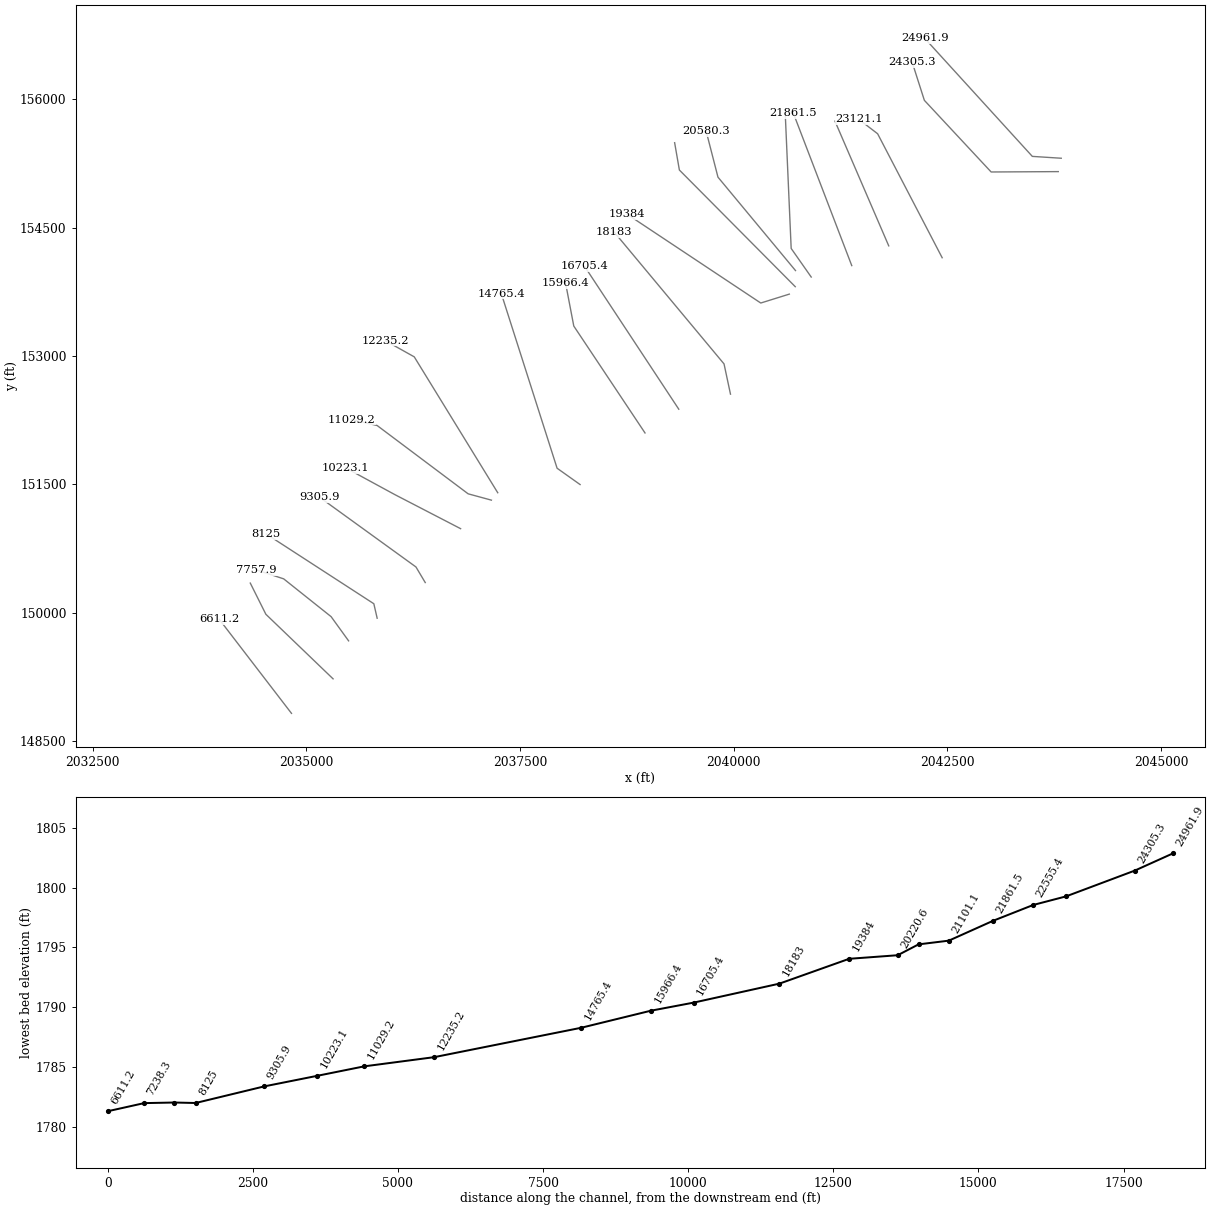
HEC-RAS study RICHCK.prj: RICHCK

--- RICHCK.g01 (geometry) --- (continued)

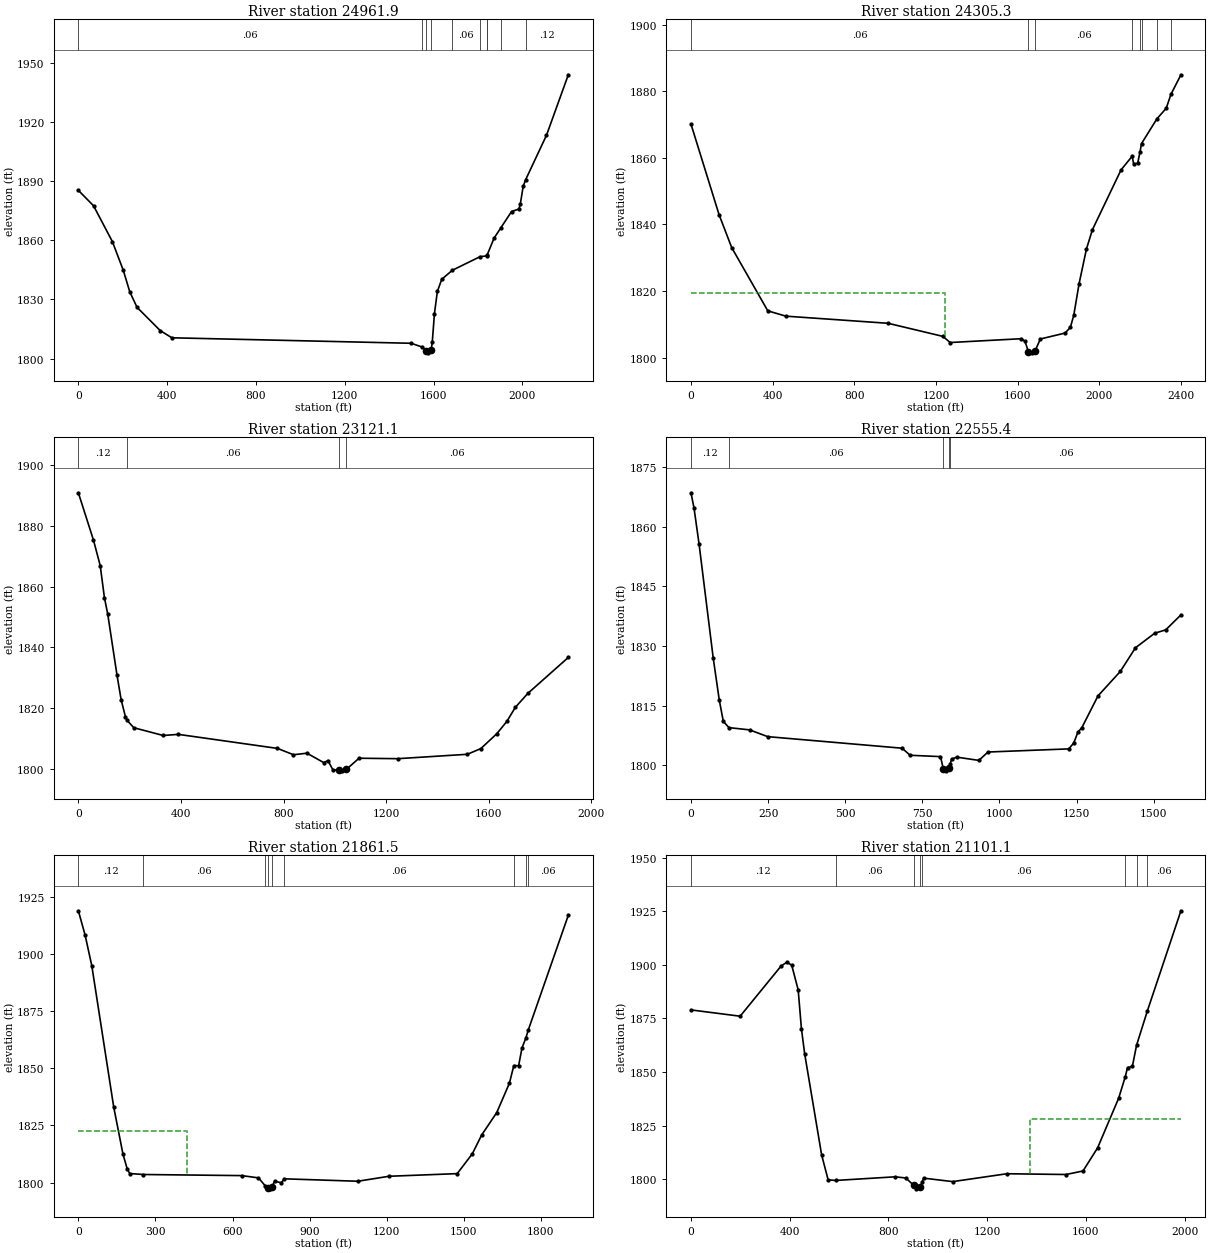
Type RM Length L Ch R = 1 ,24961.9 ,651.1,656.6,647.4
XS GIS Cut Line= 3
     2043831.964      155311.248     2043493.423       155332.95
     2042234.742      156713.158
#Sta/Elev= 30
       0 1885.46    68.5 1877.62   153.3 1859.41   202.2 1844.91   231.6 1833.92
   264.2 1826.03   368.7 1814.21   421.2 1810.53  1499.3 1807.74 1549.881805.785
  1564.9 1803.95  1574.7 1802.88 1589.22 1804.22  1594.4 1808.32  1604.2 1822.86
  1617.3 1834.06    1637 1840.25 1684.561844.829 1809.141851.725 1840.241852.176
 1840.741852.374  1872.9  1861.2 1902.841866.347  1951.6  1874.7  1984.4 1875.96
  1990.9 1878.44    2004 1887.51 2014.871890.839  2108.9 1913.44  2207.2  1944.2
#Mann= 10 ,-1 , 0
       0     .06       0 1549.88     .12       0  1564.9    .045       0
 1589.22     .12       0 1684.56     .06       0 1809.14    .016       0
 1840.24     .08       0 1840.74    .016       0 1902.84     .08       0
 2014.87     .12       0
Bank Sta=1564.9,1589.22
XS Rating Curve= 0 ,0
Exp/Cntr=0.3,0.1

Type RM Length L Ch R = 1 ,24305.3 ,1233.3,1184.2,1184.4
XS GIS Cut Line= 4
     2043797.242      155154.998     2043011.652      155150.658
     2042230.402      155988.332     2042087.173       156435.38
#Sta/Elev= 30
       0 1870.17   137.5 1842.98   199.7 1833.04   376.4 1814.06   464.8 1812.46
   965.6 1810.32    1234 1806.39    1270 1804.54  1616.9 1805.68  1636.5 1804.92
  1652.9 1801.84  1669.2 1801.44  1685.6 1801.97  1711.8  1805.6  1832.9 1807.38
    1859 1809.11  1875.4 1812.68  1901.6 1822.23  1937.6 1832.62  1966.9 1838.43
  2107.1  1856.4 2161.58 1860.51    2169 1858.18  2188.6  1858.4 2200.371861.897
 2207.641864.328  2282.81871.742  2328.8 1874.94 2351.251879.061  2400.5 1884.98
#Mann= 8 ,-1 , 0
       0     .06       0  1652.9    .045       0  1685.6     .06       0
 2161.58    .016       0 2200.37     .08       0 2207.64     .06       0
  2282.8     .08       0 2351.25     .06       0
#XS Ineff= 2 , 0
         1246.47  1819.4
Permanent Ineff=
       F       F
Bank Sta=1652.9,1685.6
XS Rating Curve= 0 ,0
Exp/Cntr=0.3,0.1

Type RM Length L Ch R = 1 ,23121.1 ,566.5,565.7,562.8
XS GIS Cut Line= 3
     2042438.735      154148.054     2041683.527      155597.707
     2041464.923      155765.081
#Sta/Elev= 30
       0 1890.99      59 1875.37    85.2 1866.98   101.6 1856.41   114.6 1850.94
   150.7 1830.82   167.1 1822.59   183.4 1817.19  190.381815.887   216.2  1813.5
   330.8 1810.94   389.8 1811.31   776.3 1806.68   838.6 1804.59     891  1805.1
   956.5    1802   972.9 1802.67   992.5 1799.57  1015.5 1799.58  1028.6 1799.28
    1045 1799.78  1094.1 1803.44  1244.8 1803.29  1516.6 1804.74  1569.1 1806.63
  1631.3 1811.53  1670.6 1815.61  1703.4 1820.22  1752.6 1824.86  1909.9 1836.68
#Mann= 4 ,-1 , 0
       0     .12       0  190.38     .06       0  1015.5    .045       0
    1045     .06       0
Bank Sta=1015.5,1045
XS Rating Curve= 0 ,0
Exp/Cntr=0.3,0.1

Type RM Length L Ch R = 1 ,22555.4 ,693.9,693.8,657.8
XS GIS Cut Line= 2
     2041813.569      154286.945     2041184.395      155745.276
#Sta/Elev= 30
       0 1868.59     9.8 1864.79    26.2 1855.72      72 1827.04    91.7 1816.42
   104.8 1811.03  123.021809.444   189.9 1808.88   248.9 1807.17   684.4 1804.26
   710.6 1802.48   808.9 1802.14     818 1799.07   825.2 1798.56   836.9 1799.23
  840.371800.308   844.9 1801.49   861.3 1802.01   933.3 1801.19   962.8  1803.3
  1224.8 1804.09  1241.1  1805.6  1254.2 1808.29  1267.3 1809.46  1319.7 1817.46
  1391.8 1823.59  1440.9 1829.55  1503.1 1833.21  1539.1 1834.07  1588.3 1837.83
#Mann= 5 ,-1 , 0
       0     .12       0  123.02     .06       0     818    .045       0
   836.9     .12       0  840.37     .06       0
Bank Sta=818,836.9
XS Rating Curve= 0 ,0
Exp/Cntr=0.3,0.1

Type RM Length L Ch R = 1 ,21861.5 ,767.4,760.5,740.1
XS GIS Cut Line= 2
     2041380.902      154055.963     2040698.284      155836.422
#Sta/Elev= 30
       0 1918.87    26.2 1908.29    52.4 1894.78   137.6 1833.04   173.6 1812.44
     190    1806   199.9 1803.92  252.941803.501   635.6 1803.02   701.1 1802.03
  726.851798.599   736.5 1797.67     747 1797.23   753.6 1798.04   763.4 1800.57
   789.6  1799.9  801.831801.613  1087.8 1800.55    1209 1802.73  1474.4 1803.88
  1533.3 1812.57  1569.4 1820.74  1628.3 1830.59  1677.5  1843.4 1694.741851.131
  1713.5 1851.11  1726.6 1858.88 1741.411863.106 1751.511866.868  1906.8  1916.9
#Mann= 9 ,-1 , 0
       0     .12       0  252.94     .06       0  726.85     .12       0
   736.5    .045       0   753.6     .12       0  801.83     .06       0
 1694.74    .016       0 1741.41     .12       0 1751.51     .06       0
#XS Ineff= 2 , 0
          423.97  1822.5
Permanent Ineff=
       F       F
Bank Sta=736.5,753.6
XS Rating Curve= 0 ,0
Exp/Cntr=0.3,0.1

Type RM Length L Ch R = 1 ,21101.1 ,505.4,520.8,532.3
XS GIS Cut Line= 3
     2040906.617       153922.36     2040672.242      154256.561
     2040602.798      155832.082
#Sta/Elev= 30
       0 1878.98   199.2 1876.05   365.7 1899.52   388.6 1901.21   408.2 1899.84
   434.4 1888.32   447.5 1870.27   460.6  1858.6   529.5 1811.34   555.7 1799.79
   585.8 1799.48   827.9 1801.18   870.5 1800.62   903.3 1797.13   913.1 1795.57
   929.5 1796.46  937.451798.964   942.6 1800.56  1060.6 1798.94  1280.3 1802.61
  1519.7 1802.25  1588.5  1803.9  1647.5 1814.65  1732.8 1837.78 1759.811847.855
  1768.8 1852.06  1788.5 1852.65 1805.411862.492 1849.431878.588  1985.2  1925.2
#Mann= 8 ,-1 , 0
       0     .12       0   585.8     .06       0   903.3    .045       0
   929.5     .12       0  937.45     .06       0 1759.81    .016       0
 1805.41     .12       0 1849.43     .06       0
#XS Ineff= 2 , 0
                         1372.53            1828
Permanent Ineff=
       F       F
Bank Sta=903.3,929.5
XS Rating Curve= 0 ,0
Exp/Cntr=0.3,0.1

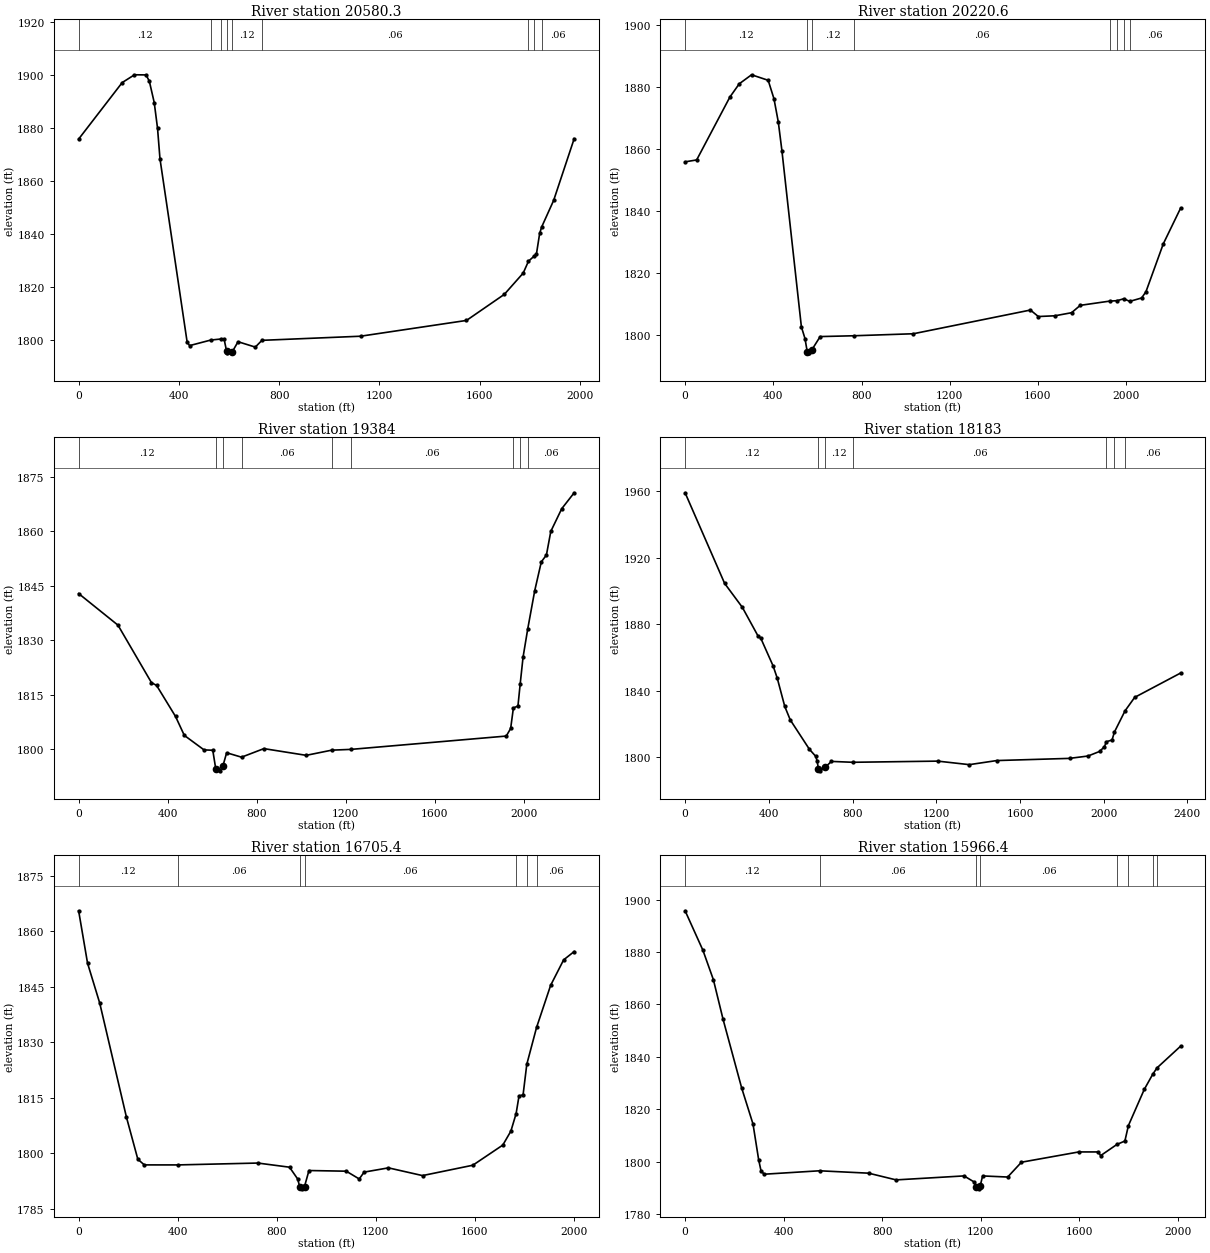
Type RM Length L Ch R = 1 ,20580.3 ,353.3,359.7,363.3
XS GIS Cut Line= 3
     2040722.806      153998.097     2039815.688      155090.111
       2039676.8      155630.042
#Sta/Elev= 30
       0  1875.8   173.8 1897.09   222.9 1900.03   268.8 1899.98     282 1897.65
   301.6 1889.57   314.8 1879.88   324.6 1868.34   432.8 1799.38   442.6 1797.98
  527.231800.078   566.61800.461   580.3 1800.46   590.2 1795.95   593.4 1795.26
   613.1 1795.67     636 1799.45   704.9 1797.42  731.37 1799.97  1124.6 1801.52
  1547.5 1807.47  1698.4 1817.29  1773.8 1825.32  1794.81829.792 1817.191831.676
  1826.3 1832.34  1839.4 1840.26 1847.691842.742  1895.2 1852.69  1977.1 1875.95
#Mann= 9 ,-1 , 0
       0     .12       0  527.23     .06       0   566.6     .12       0
   590.2    .045       0   613.1     .12       0  731.37     .06       0
  1794.8    .016       0 1817.19     .08       0 1847.69     .06       0
Bank Sta=590.2,613.1
XS Rating Curve= 0 ,0
Exp/Cntr=0.3,0.1

Type RM Length L Ch R = 1 ,20220.6 ,830.5,836.6,820.4
XS GIS Cut Line= 3
     2040719.985      153809.512       2039364.3      155173.445
     2039308.744      155492.889
#Sta/Elev= 30
       0 1855.89    52.4  1856.5   203.1 1876.76   245.7 1881.04   301.4 1883.94
   376.8 1882.16     403 1876.22   422.6 1868.77     439 1859.54   527.4 1802.72
   543.8 1798.93   553.7 1794.78   560.2 1794.35   573.3 1795.15   612.6 1799.59
  767.761799.857  1035.2  1800.5    1566 1808.14    1602 1806.05  1677.4 1806.29
  1752.7 1807.28    1792 1809.65 1925.121811.013 1959.43 1811.16 1989.411811.778
 2016.451810.929  2070.4 1812.03  2090.1 1814.06  2168.7 1829.48  2247.3 1840.99
#Mann= 8 ,-1 , 0
       0     .12       0   553.7    .045       0   573.3     .12       0
  767.76     .06       0 1925.12    .016       0 1959.43     .08       0
 1989.41     .12       0 2016.45     .06       0
Bank Sta=553.7,573.3
XS Rating Curve= 0 ,0
Exp/Cntr=0.3,0.1

Type RM Length L Ch R = 1 ,19384   ,1202.5,1201,1186.6
XS GIS Cut Line= 3
     2040650.541      153722.707     2040316.339       153618.54
     2038753.839      154655.866
#Sta/Elev= 30
       0 1842.89   176.7 1834.18   327.2 1818.34   350.1 1817.58   435.3 1809.02
   474.6 1803.82   563.2 1799.82   602.5 1799.72   615.6 1794.69   635.3 1794.05
   648.4 1795.49   664.8 1799.03  731.611797.812     832 1800.17  1022.2 1798.32
 1136.531799.746 1224.031799.964  1920.6 1803.63  1940.3 1805.72 1952.591811.366
  1973.1 1811.92 1983.341818.095    1996 1825.35 2017.081833.167  2048.5  1843.7
    2078 1851.61    2101 1853.52  2120.6 1860.01  2169.8 1866.27  2225.6 1870.65
#Mann= 9 ,-1 , 0
       0     .12       0   615.6    .045       0   648.4     .12       0
  731.61     .06       0 1136.53    .016       0 1224.03     .06       0
 1952.59    .016       0 1983.34     .12       0 2017.08     .06       0
Bank Sta=615.6,648.4
XS Rating Curve= 0 ,0
Exp/Cntr=0.3,0.1

Type RM Length L Ch R = 1 ,18183   ,1468.4,1477.6,1471
XS GIS Cut Line= 3
     2039962.117      152553.189     2039886.652      152906.735
      2038601.93      154447.533
#Sta/Elev= 30
       0 1959.14   188.9 1904.65   273.6 1890.25   348.5 1873.03   361.5 1871.73
   420.5 1855.05   440.2 1847.72   476.2 1830.69   502.5 1822.58   594.2 1804.88
   623.8 1800.75   630.3 1798.15   636.9 1793.37   646.7 1791.97   669.6 1794.16
   699.1 1797.64  800.461797.113  1207.2 1797.81    1358 1795.69  1489.1 1798.15
  1836.6 1799.46  1925.1 1800.88  1980.8 1803.65  2003.8 1806.54 2012.861809.483
  2039.8  1810.5 2051.241815.311 2101.971828.046    2148 1836.14  2367.6 1850.78
#Mann= 7 ,-1 , 0
       0     .12       0   636.9    .045       0   669.6     .12       0
  800.46     .06       0 2012.86    .016       0 2051.24     .12       0
 2101.97     .06       0
Bank Sta=636.9,669.6
XS Rating Curve= 0 ,0
Exp/Cntr=0.3,0.1

Type RM Length L Ch R = 1 ,16705.4 ,737.2,739,737.3
XS GIS Cut Line= 2
     2039357.138      152377.221     2038254.707      154048.228
#Sta/Elev= 30
       0 1865.54      36 1851.38    85.2 1840.59   193.3 1809.71   239.2 1798.37
   265.4 1796.85  399.751796.844   724.1 1797.35   851.9 1796.23   884.6 1793.07
   893.4 1790.93     901 1790.38   912.5 1791.01   930.5 1795.33  1081.2 1795.15
  1133.6 1793.05  1153.3  1794.9  1251.6 1796.05  1389.2 1793.96  1592.4 1796.76
  1713.6 1802.21  1746.3 1805.99 1767.371810.727  1779.1  1815.5  1795.5 1815.78
 1810.52 1824.05 1850.071834.026  1906.9  1845.4  1959.3 1852.27  2001.9 1854.52
#Mann= 7 ,-1 , 0
       0     .12       0  399.75     .06       0   893.4    .045       0
   912.5     .06       0 1767.37    .016       0 1810.52     .12       0
 1850.07     .06       0
Bank Sta=893.4,912.5
XS Rating Curve= 0 ,0
Exp/Cntr=0.3,0.1

Type RM Length L Ch R = 1 ,15966.4 ,1204.1,1201,1191.3
XS GIS Cut Line= 3
     2038962.173      152099.443     2038128.839      153349.443
     2038033.353      153848.575
#Sta/Elev= 30
       0 1895.71    72.2 1880.68   114.8 1869.43   154.2 1854.28   229.6 1828.13
   275.5 1814.42   298.5 1800.77   308.3 1796.44   321.5 1795.28  545.361796.582
   744.6 1795.67   856.1 1793.11  1131.7 1794.63    1171 1792.41  1180.4 1790.37
  1190.7  1789.7  1197.3 1790.84  1207.1 1794.62  1308.8  1794.2  1364.6 1799.85
  1597.4 1803.77  1676.1 1803.77  1685.9 1802.36 1751.881806.622  1784.3 1807.93
 1798.51  1813.8    1863 1827.62 1897.151833.362 1914.511835.802  2010.5  1844.1
#Mann= 8 ,-1 , 0
       0     .12       0  545.36     .06       0  1180.4    .045       0
  1197.3     .06       0 1751.88    .016       0 1798.51     .06       0
 1897.15     .12       0 1914.51     .06       0
Bank Sta=1180.4,1197.3
XS Rating Curve= 0 ,0
Exp/Cntr=0.3,0.1

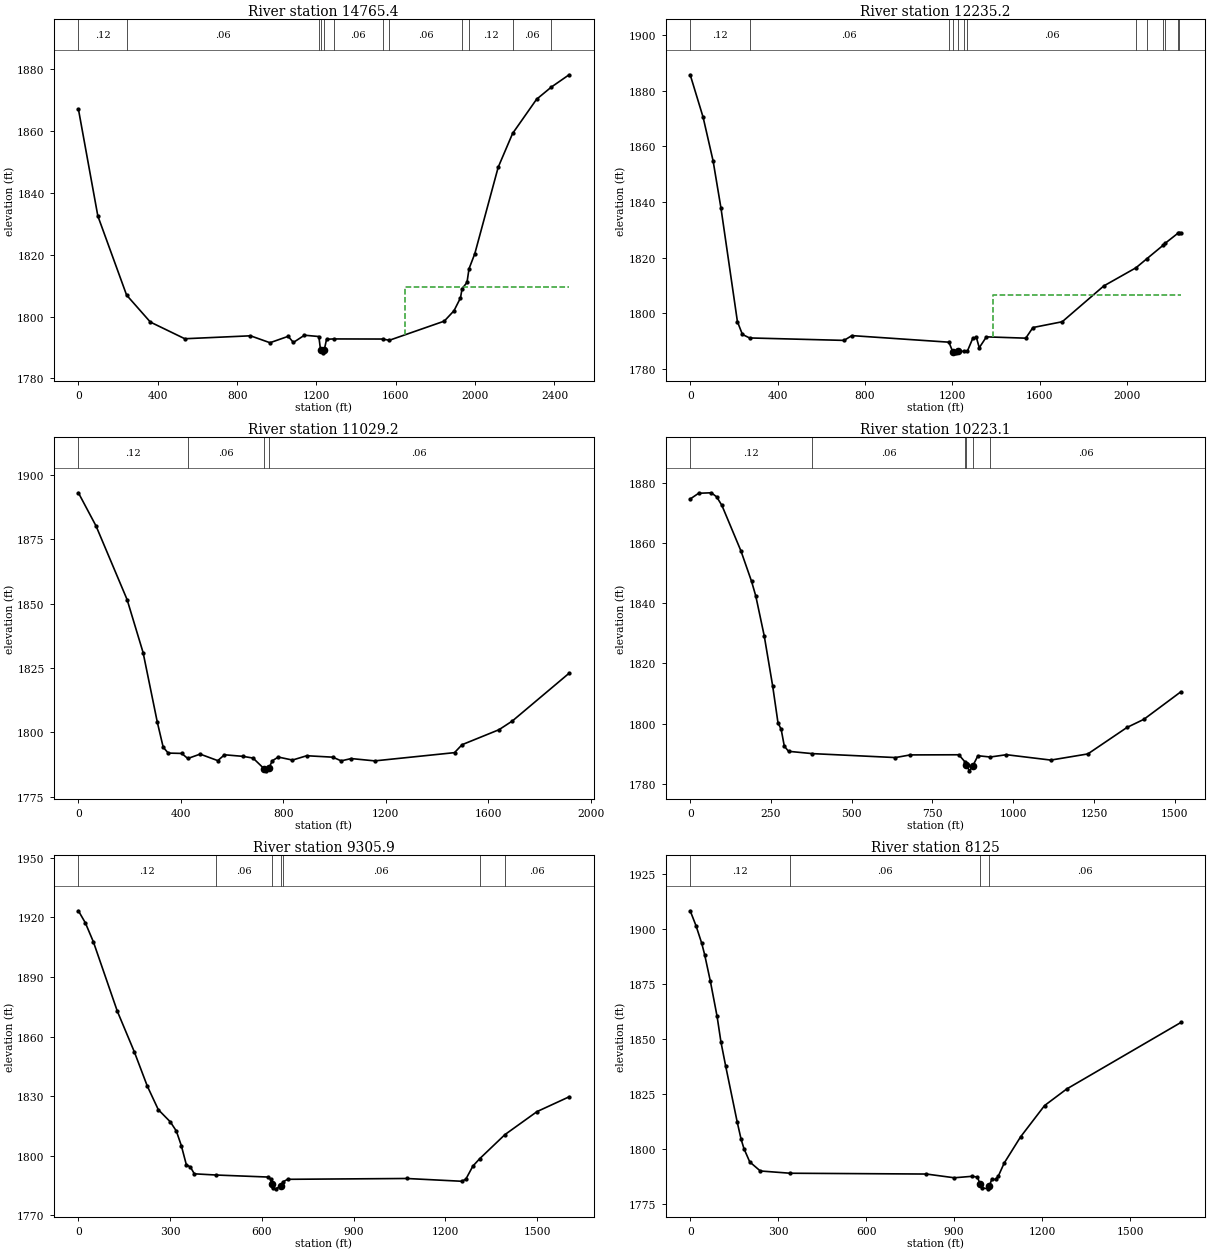
Type RM Length L Ch R = 1 ,14765.4 ,2519.1,2530.2,2524.9
XS GIS Cut Line= 3
     2038202.624      151496.144     2037933.527      151687.116
     2037280.966         153729.
#Sta/Elev= 30
       0 1867.13      98 1832.54  243.04 1806.94   362.8 1798.22   536.5 1792.83
   867.5 1793.78   965.8 1791.54  1057.6 1793.61  1083.8 1791.63  1139.6 1793.97
 1212.191793.545 1220.82  1789.1  1231.4 1788.27    1239 1789.07    1251 1792.66
 1286.051792.768 1533.691792.734 1567.411792.331  1844.3 1798.52  1893.4 1801.88
  1926.2 1806.05 1934.161809.015    1959 1811.04 1969.191815.464  1998.3 1820.32
  2116.3  1848.3 2188.871859.214  2309.7 1870.27 2384.531874.234  2473.6 1878.19
#Mann= 12 ,-1 , 0
       0     .12       0  243.04     .06       0 1212.19     .12       0
 1220.82    .045       0    1239     .12       0 1286.05     .06       0
 1533.69     .12       0 1567.41     .06       0 1934.16    .016       0
 1969.19     .12       0 2188.87     .06       0 2384.53     .12       0
#XS Ineff= 2 , 0
                         1646.41         1809.64
Permanent Ineff=
       F       F
Bank Sta=1220.82,1239
XS Rating Curve= 0 ,0
Exp/Cntr=0.3,0.1

Type RM Length L Ch R = 1 ,12235.2 ,1191,1206,1208.8
XS GIS Cut Line= 3
     2037239.082      151400.658      2036262.52        152989.2
     2035928.319      153175.832
#Sta/Elev= 30
       0 1885.69      59 1870.49   104.9 1854.77   140.9 1837.85   216.3 1797.03
   239.2 1792.42  271.911791.161   704.6 1790.28   740.6    1792 1184.981789.638
  1202.7  1786.2  1215.8 1785.81  1226.7 1786.31 1255.081786.361 1269.251786.361
  1294.5 1791.06  1310.9 1791.33    1324 1787.65  1356.8 1791.55    1537 1791.08
  1569.8  1794.9  1704.1 1796.98  1894.2 1809.83 2041.811816.366 2092.481819.666
 2167.521824.538 2176.76 1825.24 2235.191828.846 2237.341828.807  2247.5  1828.9
#Mann= 13 ,-1 , 0
       0     .12       0  271.91     .06       0 1184.98     .12       0
  1202.7    .045       0  1226.7     .06       0 1255.08     .08       0
 1269.25     .06       0 2041.81    .016       0 2092.48     .06       0
 2167.52     .12       0 2176.76     .08       0 2235.19     .06       0
 2237.34     .08       0
#XS Ineff= 2 , 0
                         1387.79         1806.43
Permanent Ineff=
       F       F
Bank Sta=1202.7,1226.7
XS Rating Curve= 0 ,0
Exp/Cntr=0.3,0.1

Type RM Length L Ch R = 1 ,11029.2 ,797.9,806.1,807
XS GIS Cut Line= 4
     2037165.298      151313.853     2036893.076      151387.811
     2035828.492      152186.248     2035533.353      152255.693
#Sta/Elev= 30
       0 1893.11    68.9 1880.21   190.2 1851.59   252.6 1831.03   308.3 1803.89
   331.2  1794.2   350.9 1791.94   403.4 1791.81  427.141789.837   475.5 1791.54
   544.3 1789.01   570.5 1791.28   642.6 1790.67     682    1790   724.3 1785.94
   731.1 1785.04   744.2 1786.26   757.4 1788.96   780.3  1790.4     836 1789.23
   891.7 1790.91   993.3 1790.35  1026.1 1788.92  1065.4 1789.81  1157.2 1788.91
  1468.6 1792.11  1498.1  1795.2  1642.2 1801.02  1694.3  1804.4    1916 1822.97
#Mann= 4 ,-1 , 0
       0     .12       0  427.14     .06       0   724.3    .045       0
   744.2     .06       0
Bank Sta=724.3,744.2
XS Rating Curve= 0 ,0
Exp/Cntr=0.3,0.1

Type RM Length L Ch R = 1 ,10223.1 ,916.4,917.2,904
XS GIS Cut Line= 3
     2036804.744      150980.449     2036034.061       151379.27
     2035461.874      151690.186
#Sta/Elev= 30
       0 1874.75    26.2 1876.66    65.5 1876.82    81.9 1875.46    98.2 1872.61
   157.2 1857.44   189.9 1847.34     203 1842.48   229.2 1829.19   255.4 1812.45
   271.8 1800.24   281.6 1798.08   291.4 1792.46   304.5 1790.75  377.911789.984
   635.3 1788.67   681.1 1789.55   831.7  1789.6  850.221787.275   854.7 1786.16
   864.5 1784.25   875.3    1786   890.7 1789.28  928.891788.853     979 1789.62
  1116.5 1787.83    1231 1789.88  1352.1 1798.69  1404.4  1801.4    1519 1810.57
#Mann= 6 ,-1 , 0
       0     .12       0  377.91     .06       0  850.22     .12       0
   854.7    .045       0   875.3     .12       0  928.89     .06       0
Bank Sta=854.7,875.3
XS Rating Curve= 0 ,0
Exp/Cntr=0.3,0.1

Type RM Length L Ch R = 1 ,9305.9  ,1178.3,1180.9,1180.8
XS GIS Cut Line= 3
     2036390.992      150350.311     2036282.485      150532.603
     2035154.013      151348.575
#Sta/Elev= 30
       0 1923.38    22.8 1917.29      49 1907.75   127.3 1872.81   182.8 1852.39
   225.2 1835.16   261.3 1823.24   300.6 1817.09   320.3 1812.48   336.6 1805.14
     353 1795.51   366.1 1794.38   379.2 1790.92  448.521790.332   621.7 1789.29
   628.3 1788.24   631.6 1785.58   634.8 1783.68   644.7 1783.36     661 1784.66
  668.851786.841     684 1788.16  1073.9 1788.57  1254.1 1787.17  1267.2 1788.27
  1290.2 1794.84 1312.291798.518    1395 1810.68  1499.9 1822.26  1604.7 1829.69
#Mann= 7 ,-1 , 0
       0     .12       0  448.52     .06       0   631.6    .045       0
     661     .08       0  668.85     .06       0 1312.29     .08       0
    1395     .06       0
Bank Sta=631.6,661
XS Rating Curve= 0 ,0
Exp/Cntr=0.3,0.1

Type RM Length L Ch R = 1 ,8125    ,371.1,367.2,362.6
XS GIS Cut Line= 3
     2035828.492      149933.644      2035789.43      150102.915
      2034530.54      150918.519
#Sta/Elev= 30
       0  1908.4    19.7 1901.67    39.3 1893.65    49.2 1888.51    68.8 1876.38
    91.8 1860.35   104.9 1848.74   121.3 1837.61   160.6 1812.21   173.7 1804.49
   183.5 1800.22   203.2  1794.2   239.2 1790.09  341.041789.064   805.8  1788.7
   900.8    1787   959.8 1787.65   979.4 1787.36   989.2 1784.08   995.8 1782.39
  1015.4 1781.97  1020.1 1783.21  1028.5 1786.26  1041.6 1786.24  1051.4 1787.88
  1071.1 1793.71  1126.8 1805.58  1208.7 1819.83    1284 1827.35  1673.7 1857.61
#Mann= 4 ,-1 , 0
       0     .12       0  341.04     .06       0   989.2    .045       0
  1020.1     .06       0
Bank Sta=989.2,1020.1
XS Rating Curve= 0 ,0
Exp/Cntr=0.3,0.1

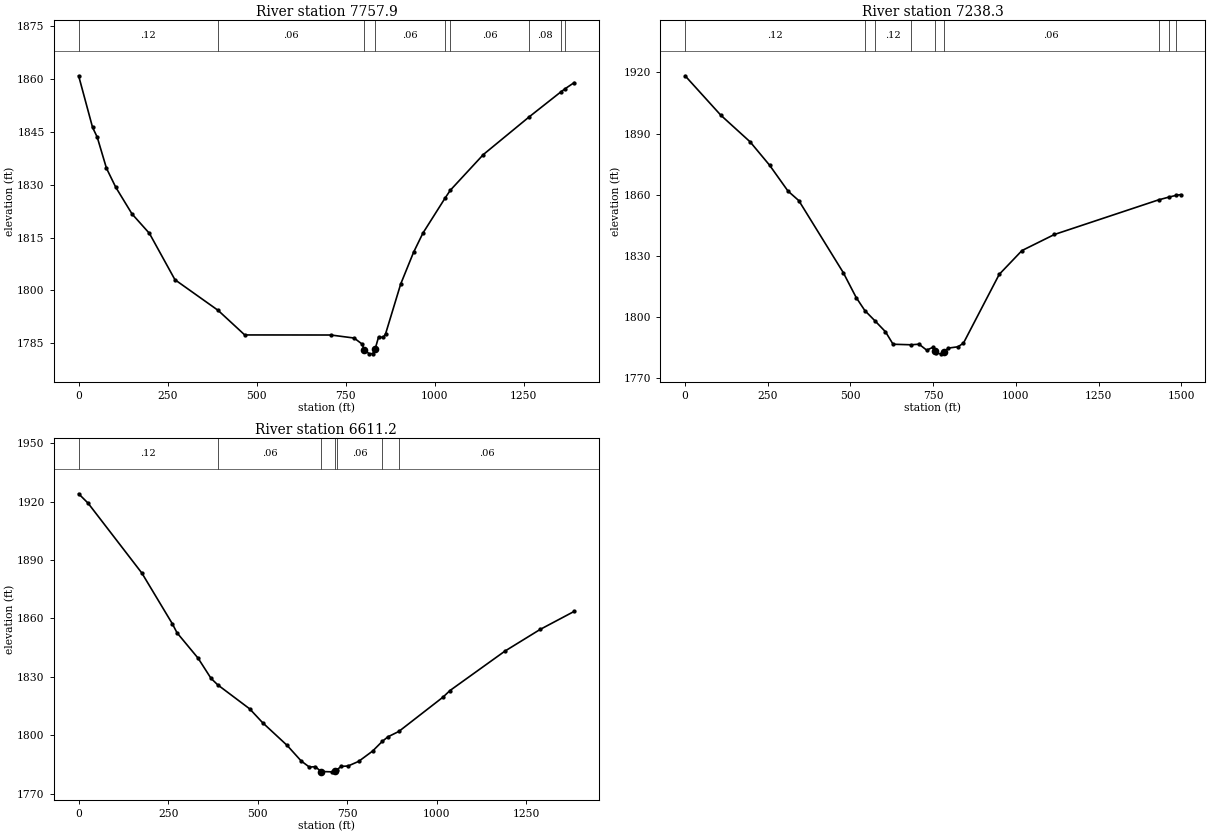
Type RM Length L Ch R = 1 ,7757.9  ,517.7,519.6,519
XS GIS Cut Line= 4
     2035494.291      149668.887     2035289.885      149951.597
     2034734.742      150393.714     2034417.902       150497.88
#Sta/Elev= 30
       0 1860.88    39.1 1846.25    52.2 1843.48    78.2 1834.65   104.3 1829.26
     150 1821.69   198.9 1816.17   270.6 1803.03  391.941794.331   466.6 1787.37
   708.6 1787.35     774 1786.49   796.9 1784.73   801.7 1783.23   816.5 1782.01
   826.4  1782.1   832.9 1783.37   842.7 1786.82   855.8 1786.65   862.3 1787.69
   904.8 1801.82   940.8 1810.78     967 1816.22 1029.991826.275 1044.381828.438
    1137 1838.54 1266.211849.266    13561856.412 1367.491857.265  1392.1 1858.94
#Mann= 9 ,-1 , 0
       0     .12       0  391.94     .06       0   801.7    .045       0
   832.9     .06       0 1029.99     .08       0 1044.38     .06       0
 1266.21     .08       0    1356     .06       0 1367.49     .08       0
Bank Sta=801.7,832.9
XS Rating Curve= 0 ,0
Exp/Cntr=0.3,0.1

Type RM Length L Ch R = 1 ,7238.3  ,628.4,627.1,620.3
XS GIS Cut Line= 3
     2035312.867      149224.443     2034526.409      149979.651
     2034344.117      150344.235
#Sta/Elev= 30
       0 1918.37     108 1899.02   196.5 1885.97   255.4  1874.5   311.1  1861.8
   343.8 1857.12     478 1821.85   517.3 1809.56  543.45 1803.17  574.311798.098
   605.8 1792.78   628.7 1786.67  683.37  1786.4   707.2  1786.7   730.2 1783.78
   749.8  1785.2   756.4 1783.58   759.6 1782.37   772.7 1781.96   783.1 1782.95
   795.7 1784.77   825.1 1785.43   841.5 1787.23   949.6 1820.95  1018.3 1832.62
  1116.4 1840.51 1431.19 1857.49 1461.751858.819 1485.121859.739    1498 1860.07
#Mann= 9 ,-1 , 0
       0     .12       0  543.45     .06       0  574.31     .12       0
  683.37     .06       0   756.4    .045       0   783.1     .06       0
 1431.19     .08       0 1461.75     .06       0 1485.12     .08       0
Bank Sta=756.4,783.1
XS Rating Curve= 0 ,0
Exp/Cntr=0.3,0.1

Type RM Length L Ch R = 1 ,6611.2  ,386.3,388.1,388.4
XS GIS Cut Line= 2
      2034826.31      148820.923     2033982.602       149918.69
#Sta/Elev= 30
       0    1924    26.2 1919.22   176.8 1883.27   261.8 1857.28   274.9 1852.65
   333.9 1839.58   369.9 1829.26  388.771825.905   477.9 1813.61   513.9 1806.53
   582.6 1794.84   621.9 1786.84   644.8 1783.71   661.2 1783.95   677.1 1781.45
     707 1781.28   716.8  1781.7  721.651782.305   733.2 1784.07   752.8 1784.28
   782.3 1786.64   821.6 1791.98  848.091796.868   864.1 1799.25  894.471801.993
  1017.9  1819.6  1037.6 1823.02  1191.4 1843.29  1289.6 1854.39  1384.5 1863.63
#Mann= 7 ,-1 , 0
       0     .12       0  388.77     .06       0   677.1    .045       0
   716.8     .08       0  721.65     .06       0  848.09     .12       0
  894.47     .06       0
Bank Sta=677.1,716.8
XS Rating Curve= 0 ,0
Exp/Cntr=0.3,0.1