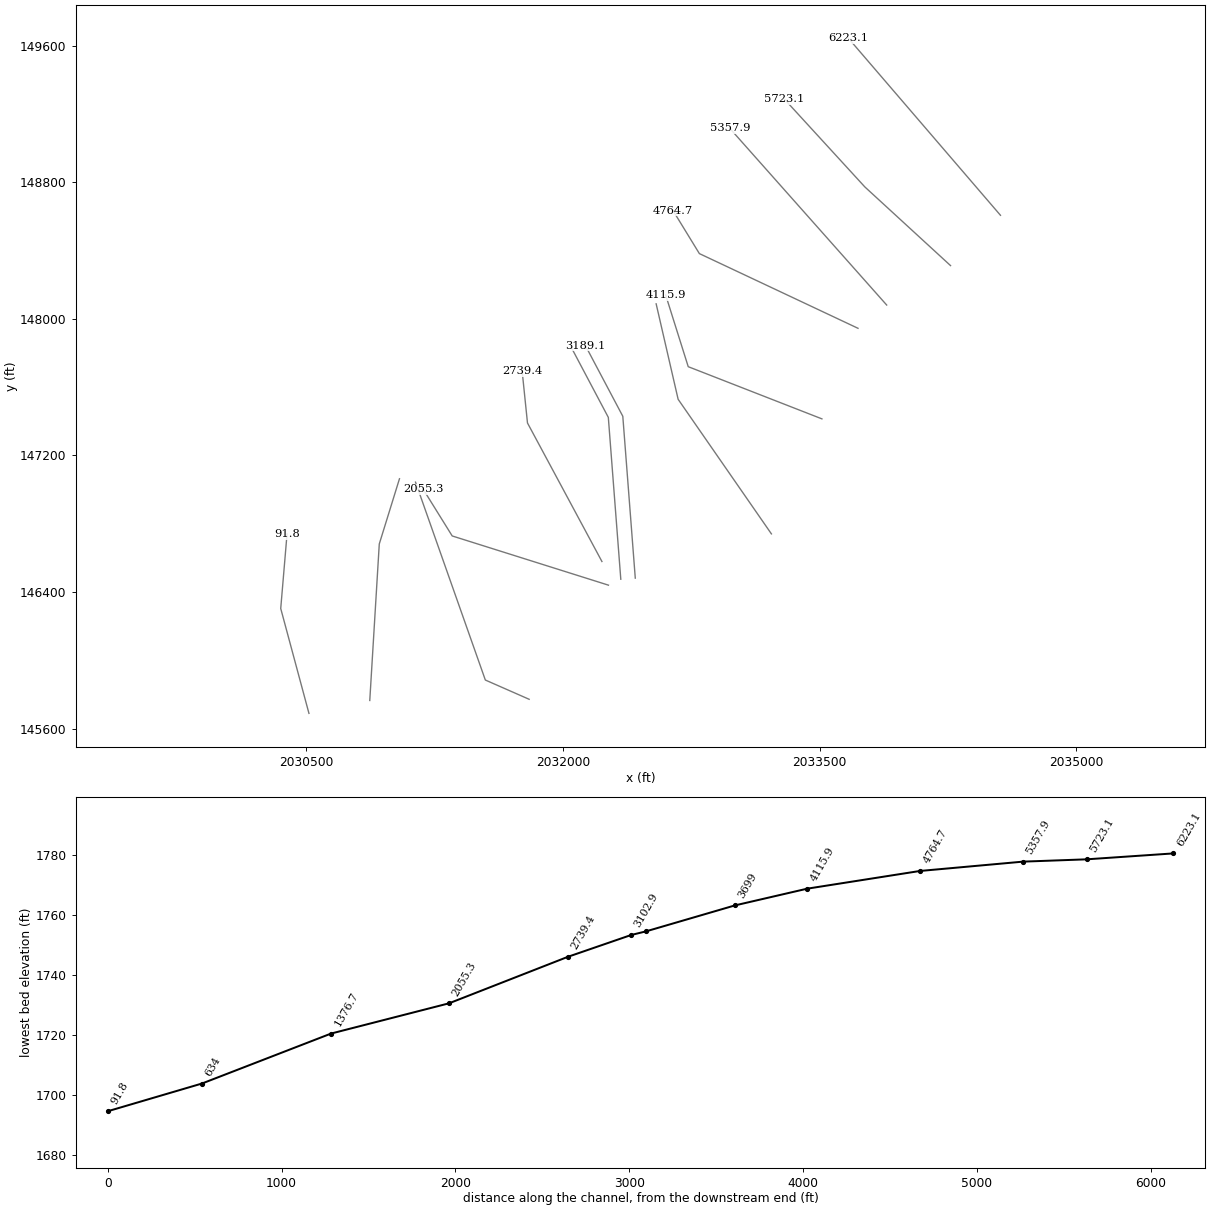
HEC-RAS study RICHCK.prj: RICHCK

--- RICHCK.g01 (geometry) --- (continued)

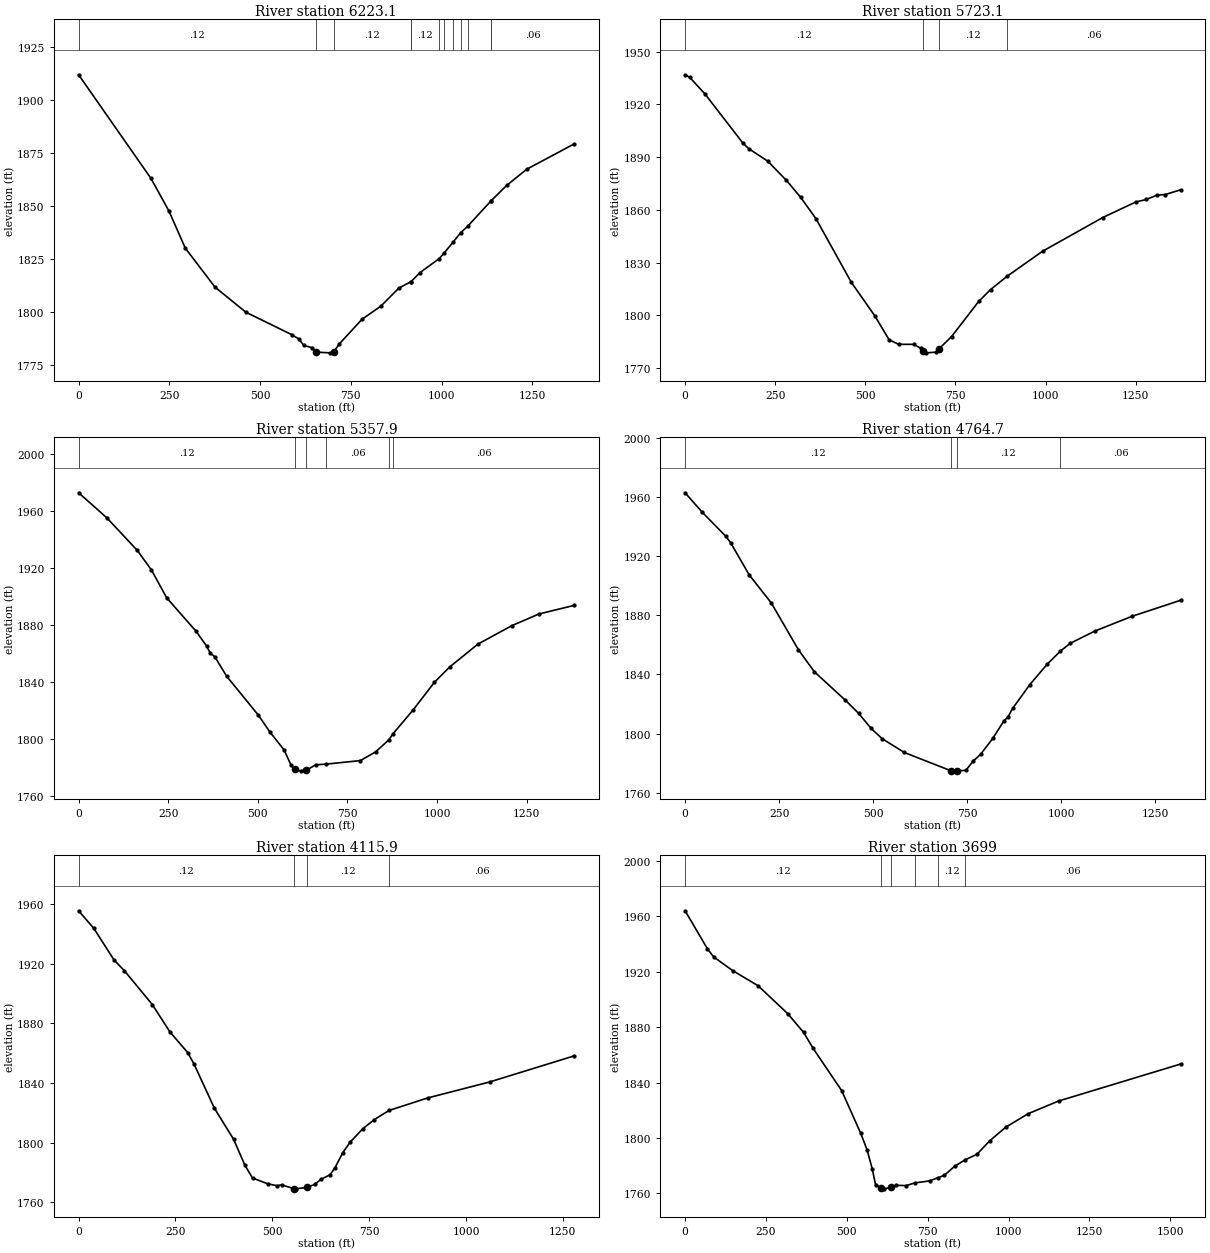
Type RM Length L Ch R = 1 ,6223.1  ,496.7,500,500.2
XS GIS Cut Line= 3
     2034556.083      148605.865     2034111.919      149124.059
     2033667.755      149642.252
#Sta/Elev= 30
       0 1911.82   199.2 1862.95   248.2 1847.77   293.9 1830.04   375.5 1811.71
   460.4 1799.88   587.8  1789.2   607.4 1787.13   620.4 1784.18   643.3 1783.09
   653.1 1781.03   692.3 1780.69   702.1 1781.05   718.4 1784.96   780.5  1796.5
   832.7 1802.74   881.7 1811.16   915.71814.289  915.851814.309   940.5 1818.55
  993.511825.155 1006.631827.743 1032.411833.067 1052.021837.259 1071.321840.319
 1135.011852.192 1135.981852.365  1178.9 1859.62  1234.4 1867.28    1365 1879.22
#Mann= 12 ,-1 , 0
       0     .12       0   653.1    .045       0   702.1     .12       0
   915.7     .06       0  915.85     .12       0  993.51     .06       0
 1006.63     .12       0 1032.41     .08       0 1052.02     .12       0
 1071.32     .06       0 1135.01     .08       0 1135.98     .06       0
Bank Sta=653.1,702.1
XS Rating Curve= 0 ,0
Exp/Cntr=0.3,0.1

Type RM Length L Ch R = 1 ,5723.1  ,367.2,365.2,364.8
XS GIS Cut Line= 3
     2034264.174      148311.318     2033763.448       148771.99
      2033294.84      149284.425
#Sta/Elev= 30
       0 1936.83    13.1 1935.33    55.6 1925.79   160.3    1898   176.6  1894.8
     229 1887.76   281.3 1876.74   320.6 1867.15   363.1 1854.98   461.2 1818.78
   526.7 1799.64   565.9 1786.19   592.1 1783.55   634.6 1783.55   654.2 1781.22
   660.8 1779.61   667.3 1778.71   696.8 1779.09   703.3 1780.74   739.4    1788
   814.7 1807.98   847.4 1814.67  893.481822.285   991.6 1836.46  1158.6 1855.64
  1250.3 1864.48  1279.8 1865.93  1309.3 1868.41  1332.2 1868.73  1374.8 1871.42
#Mann= 4 ,-1 , 0
       0     .12       0   660.8    .045       0   703.3     .12       0
  893.48     .06       0
Bank Sta=660.8,703.3
XS Rating Curve= 0 ,0
Exp/Cntr=0.3,0.1

Type RM Length L Ch R = 1 ,5357.9  ,581.6,593.1,600.2
XS GIS Cut Line= 2
     2033890.992      148080.346     2032974.326      149115.068
#Sta/Elev= 30
       0 1972.83    78.6 1955.29   163.8 1932.39   203.1 1918.71   245.7 1899.18
   327.6 1875.78   357.1 1865.33   366.9 1860.58     380 1857.86   412.7 1844.34
   501.2 1817.02     534 1805.04   573.2  1792.6   592.9 1781.72   602.7 1778.95
   619.1 1777.94   635.5 1778.45   661.7 1782.17  691.041782.669   786.2 1785.13
   828.8 1791.29  865.341799.689   876.9 1803.89   933.6 1820.77   992.6 1840.04
  1035.1 1850.74  1113.8 1866.75  1208.8 1879.73  1284.1 1887.87  1382.4 1893.91
#Mann= 6 ,-1 , 0
       0     .12       0   602.7    .045       0   635.5     .12       0
  691.04     .06       0  865.34     .12       0   876.9     .06       0
Bank Sta=602.7,635.5
XS Rating Curve= 0 ,0
Exp/Cntr=0.3,0.1

Type RM Length L Ch R = 1 ,4764.7  ,647.7,648.8,649.5
XS GIS Cut Line= 3
     2033723.457      147944.061     2032796.374      148381.561
     2032643.596      148631.561
#Sta/Elev= 30
       0 1962.73    45.8 1949.53   108.1 1933.38   121.2 1928.96   170.3 1907.31
   229.3 1888.26   301.3 1856.71   343.9 1841.74   425.8 1822.66   461.8 1813.59
   494.6 1803.52     524 1796.59     583 1787.23     707 1774.88     714 1774.82
     722 1774.88   746.7  1775.1   766.4 1781.44     786 1785.97   818.8 1796.88
   848.3 1808.71   858.1 1810.91   871.2 1817.02     917 1833.09   962.9  1846.8
  997.951855.666  1025.1 1861.09  1090.2  1869.3  1187.9 1879.17  1318.1  1890.1
#Mann= 4 ,-1 , 0
       0     .12       0     707    .045       0     722     .12       0
  997.95     .06       0
Bank Sta=707,722
XS Rating Curve= 0 ,0
Exp/Cntr=0.3,0.1

Type RM Length L Ch R = 1 ,4115.9  ,428.6,416.9,403.1
XS GIS Cut Line= 3
      2033512.52      147413.679      2032731.27      147719.235
     2032599.326      148139.373
#Sta/Elev= 30
       0 1955.54    39.3 1943.69    91.8 1922.36     118 1915.36   190.1 1892.62
   235.9 1874.16   281.8 1860.27   298.2  1852.5   350.6 1822.95   399.8 1802.27
   429.3  1784.7   448.9 1776.14   488.2  1772.3   511.2 1771.01   524.3 1771.53
     556 1769.01   560.3  1768.9   589.8 1769.86   609.5  1771.9   625.9 1775.32
   648.8 1778.34   661.9  1783.1   681.6 1793.08   701.2 1800.32     734 1809.33
   763.5 1815.44  801.771821.552   900.9  1829.9  1060.7 1840.61  1279.2 1858.14
#Mann= 4 ,-1 , 0
       0     .12       0     556    .045       0   589.8     .12       0
  801.77     .06       0
Bank Sta=556,589.8
XS Rating Curve= 0 ,0
Exp/Cntr=0.3,0.1

Type RM Length L Ch R = 1 ,3699    ,521.6,510,497.3
XS GIS Cut Line= 3
     2033217.381      146740.068     2032672.242      147528.262
      2032543.77       148087.29
#Sta/Elev= 30
       0 1964.04    68.7 1936.73    88.3 1930.73   147.2 1920.83   225.7 1909.92
   317.3 1889.75   366.3 1876.26   395.8  1864.7   484.1 1834.19     543 1803.34
   562.6 1791.41   578.9 1777.48   588.7 1766.27   605.1 1763.86   614.9 1763.29
   635.6 1764.35   650.9 1765.89   683.6  1765.6   709.8 1767.56   755.6    1769
  781.211771.279   801.4 1773.05   834.1 1779.73  866.041784.251   902.7 1788.31
     942 1798.04   991.1 1807.75    1060 1817.47    1155 1826.72    1532  1853.4
#Mann= 6 ,-1 , 0
       0     .12       0   605.1    .045       0   635.6     .12       0
   709.8     .06       0  781.21     .12       0  866.04     .06       0
Bank Sta=605.1,635.6
XS Rating Curve= 0 ,0
Exp/Cntr=0.3,0.1

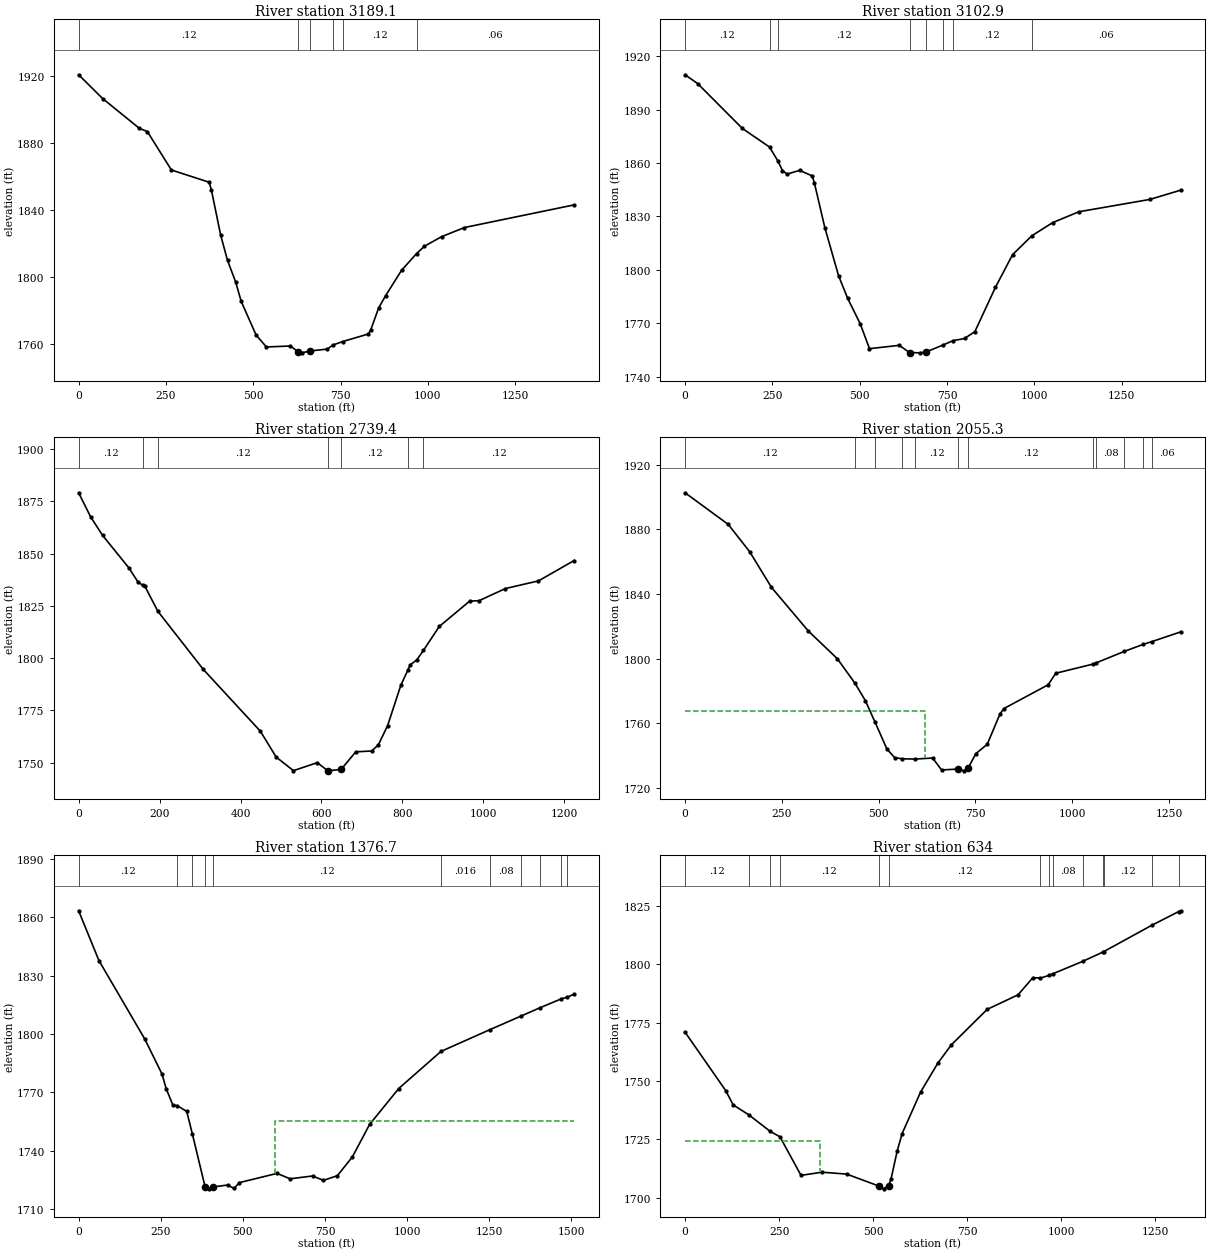
Type RM Length L Ch R = 1 ,3189.1  ,86.4,86.2,86.6
XS GIS Cut Line= 3
     2032421.808      146480.953     2032348.892       147428.87
     2032130.447      147842.591
#Sta/Elev= 30
       0 1920.81    68.8  1906.6   173.8 1888.81   196.7 1886.87   265.6  1863.9
   373.7 1856.59   380.3 1851.76   406.5 1825.08   426.2 1809.88   449.1 1797.21
   465.5 1785.36   508.1 1765.24   537.6 1758.15   606.5 1758.73   629.4 1755.02
   639.3 1754.64   662.2 1755.74   711.4 1756.87  728.211759.323  755.941761.393
   829.4  1765.9     836 1768.23   858.9 1781.48   878.6 1788.74   924.5 1803.96
  967.291813.936     990 1818.34    1039 1824.05  1104.5 1829.53  1418.6 1843.06
#Mann= 6 ,-1 , 0
       0     .12       0   629.4    .045       0   662.2     .12       0
  728.21    .016       0  755.94     .12       0  967.29     .06       0
Bank Sta=629.4,662.2
XS Rating Curve= 0 ,0
Exp/Cntr=0.3,0.1

Type RM Length L Ch R = 1 ,3102.9  ,353.6,363.4,372.6
XS GIS Cut Line= 3
     2032337.173      146474.443     2032264.256       147422.36
     2032045.812       147836.08
#Sta/Elev= 30
       0  1909.6    36.1 1904.63   163.9 1879.47  241.731868.998  265.061861.381
   278.7 1855.83   291.8 1853.82   327.8  1855.9   363.9  1852.8   370.4 1848.64
     400 1823.76   439.3 1796.74   465.5 1783.97   501.6  1769.6   527.8 1755.76
     613 1757.62   642.6  1753.6   672.1 1753.41   688.4 1753.81  737.131757.685
  766.371760.206   799.9 1761.48   829.4 1765.27   888.4  1790.2   937.6  1808.6
  992.811819.182  1052.1 1826.54  1127.4 1832.66  1330.2 1839.57  1418.6 1844.78
#Mann= 8 ,-1 , 0
       0     .12       0  241.73    .016       0  265.06     .12       0
   642.6    .045       0   688.4     .12       0  737.13    .016       0
  766.37     .12       0  992.81     .06       0
Bank Sta=642.6,688.4
XS Rating Curve= 0 ,0
Exp/Cntr=0.3,0.1

Type RM Length L Ch R = 1 ,2739.4  ,666.6,684.1,701.3
XS GIS Cut Line= 3
       2032226.9      146578.228     2031791.817       147389.59
     2031760.814      147691.838
#Sta/Elev= 30
       0 1879.15    29.5 1867.69      59 1858.82   124.5 1843.14   147.4 1836.24
  159.581834.839   163.8 1834.42  195.741822.462     308 1794.66   448.9 1765.13
   488.2 1752.71   530.8 1746.22   589.7 1750.04     616 1746.13   648.7 1746.82
   684.8 1755.23   724.1 1755.62   740.5 1758.51   763.4  1767.7   796.2 1787.07
  813.251794.219   819.1 1796.81   835.5 1799.16  851.891803.719   891.2  1815.2
   966.4 1827.35   989.3 1827.51  1054.6 1833.34  1136.3    1837  1224.5 1846.75
#Mann= 7 ,-1 , 0
       0     .12       0  159.58    .016       0  195.74     .12       0
     616    .045       0   648.7     .12       0  813.25    .016       0
  851.89     .12       0
Bank Sta=616,648.7
XS Rating Curve= 0 ,0
Exp/Cntr=0.3,0.1

Type RM Length L Ch R = 1 ,2055.3  ,700.2,678.6,654.3
XS GIS Cut Line= 3
     2032265.124      146439.721      2031351.93      146727.915
     2031182.008      147002.004
#Sta/Elev= 30
       0 1902.55   111.5 1882.98   167.2 1865.96     223 1844.08   318.1 1817.13
   393.5 1799.86  438.911784.732   465.7    1774  490.941760.545   521.4 1744.05
   541.1 1738.79  560.681738.024  594.651737.876   639.5  1738.5   662.4 1731.13
   705.1 1731.67   721.5 1730.58   731.3 1732.35     751 1741.19   780.5    1747
   813.3 1765.67   823.1 1769.04   937.9 1783.81   957.6 1790.94 1053.121796.562
 1062.611797.434 1135.061804.499 1183.751808.815 1206.431810.564  1280.1  1816.5
#Mann= 12 ,-1 , 0
       0     .12       0  438.91    .016       0  490.94     .12       0
  560.68    .016       0  594.65     .12       0   705.1    .045       0
   731.3     .12       0 1053.12     .06       0 1062.61     .08       0
 1135.06     .06       0 1183.75     .08       0 1206.43     .06       0
#XS Ineff= 2 , 0
          620.46 1767.86
Permanent Ineff=
       F       F
Bank Sta=705.1,731.3
XS Rating Curve= 0 ,0
Exp/Cntr=0.3,0.1

Type RM Length L Ch R = 1 ,1376.7  ,749.8,742.7,733.9
XS GIS Cut Line= 3
     2031801.582      145771.318     2031545.506      145884.165
      2031137.52      147043.019
#Sta/Elev= 30
       0 1863.33    61.8 1837.75   201.7 1797.32   253.8 1779.44   266.8 1771.76
   286.4  1763.7  300.351763.151     329 1760.25  346.231748.657   384.7 1721.66
   397.8 1720.47   409.9 1721.48   453.5 1722.41   473.1 1720.68   489.5 1723.68
   604.2 1728.41   643.5 1725.62   712.3 1727.08   745.1 1724.82   787.6 1727.23
   833.5 1736.94   885.9 1753.61   974.4 1772.02 1102.871791.067 1250.72 1802.17
 1347.311809.286 1404.361813.499 1467.491817.966 1486.881818.929  1508.4 1820.48
#Mann= 11 ,-1 , 0
       0     .12       0  300.35    .016       0  346.23     .12       0
   384.7    .045       0   409.9     .12       0 1102.87    .016       0
 1250.72     .08       0 1347.31     .06       0 1404.36     .08       0
 1467.49     .06       0 1486.88     .08       0
#XS Ineff= 2 , 0
                          598.76         1755.24
Permanent Ineff=
       F       F
Bank Sta=384.7,409.9
XS Rating Curve= 0 ,0
Exp/Cntr=0.3,0.1

Type RM Length L Ch R = 1 ,634     ,534.9,542.2,549.2
XS GIS Cut Line= 3
     2030870.159      145764.373     2030925.714       146681.04
      2031043.77      147062.985
#Sta/Elev= 30
       0 1770.85   108.2 1745.82   127.9 1739.72   169.41735.481  226.481728.379
   252.31726.062   308.3 1709.55   364.1 1710.89   429.7 1710.09   514.9    1705
     528 1703.77   541.2 1705.13   547.7 1707.92   564.1 1719.94   577.2 1727.42
   626.4 1745.22   672.4 1757.65   708.4 1765.49   803.6 1780.66   885.6 1786.87
   924.9 1794.22  945.261794.048  967.911795.217   978.41795.903 1058.271801.259
  1112.3 1805.26 1113.951805.425 1241.411816.674 1312.491822.504  1318.1 1822.88
#Mann= 14 ,-1 , 0
       0     .12       0   169.4     .06       0  226.48    .016       0
   252.3     .12       0   514.9    .045       0   541.2     .12       0
  945.26    .016       0  967.91     .12       0   978.4     .08       0
 1058.27     .12       0  1112.3     .08       0 1113.95     .12       0
 1241.41     .08       0 1312.49    .016       0
#XS Ineff= 2 , 0
           359.3 1724.17
Permanent Ineff=
       F       F
Bank Sta=514.9,541.2
XS Rating Curve= 0 ,0
Exp/Cntr=0.3,0.1

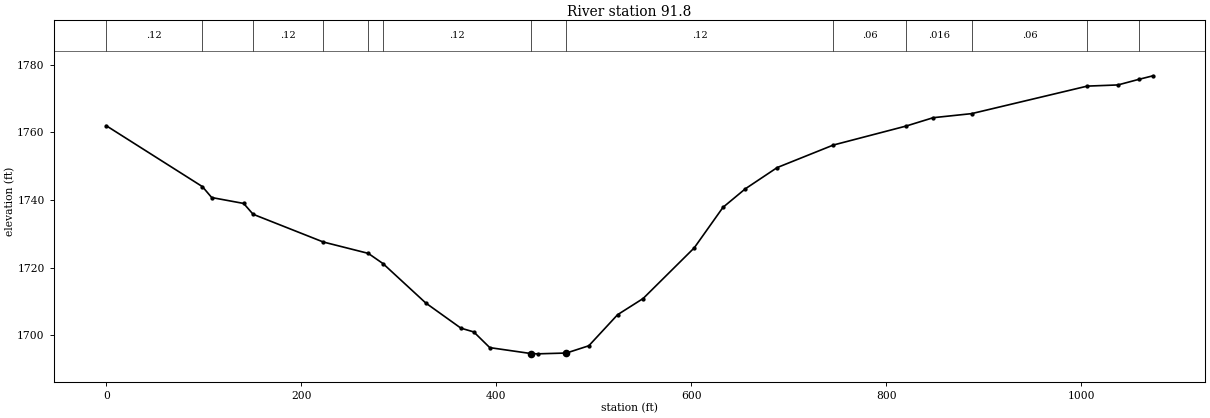
Type RM Length L Ch R = 1 ,91.8    ,87.2,91.8,96.3
XS GIS Cut Line= 3
      2030514.69      145688.853      2030349.76      146303.002
     2030386.652        146739.2
#Sta/Elev= 30
       0    1762   98.66 1743.97   108.2 1740.74     141 1738.99  150.651735.793
  222.671727.583  268.791724.221  283.851721.208   327.8 1709.53   363.8  1702.1
     377 1700.98   393.4 1696.34     436 1694.57   442.5  1694.5     472 1694.74
     495 1696.89   524.5 1706.08   550.7 1710.87   603.1 1725.85   632.6 1737.84
   655.5 1743.32   688.2 1749.61  745.791756.272  820.341761.881   848.2 1764.36
  887.57 1765.56 1006.161773.703  1037.7 1774.05 1059.551775.739  1073.7 1776.76
#Mann= 13 ,-1 , 0
       0     .12       0   98.66     .08       0  150.65     .12       0
  222.67    .016       0  268.79     .08       0  283.85     .12       0
     436    .045       0     472     .12       0  745.79     .06       0
  820.34    .016       0  887.57     .06       0 1006.16     .08       0
 1059.55     .06       0
Bank Sta=436,472
XS Rating Curve= 0 ,0
Exp/Cntr=0.3,0.1

Chan Stop Cuts=-1
Use User Specified Reach Order=0
Composite Channel Slope=5